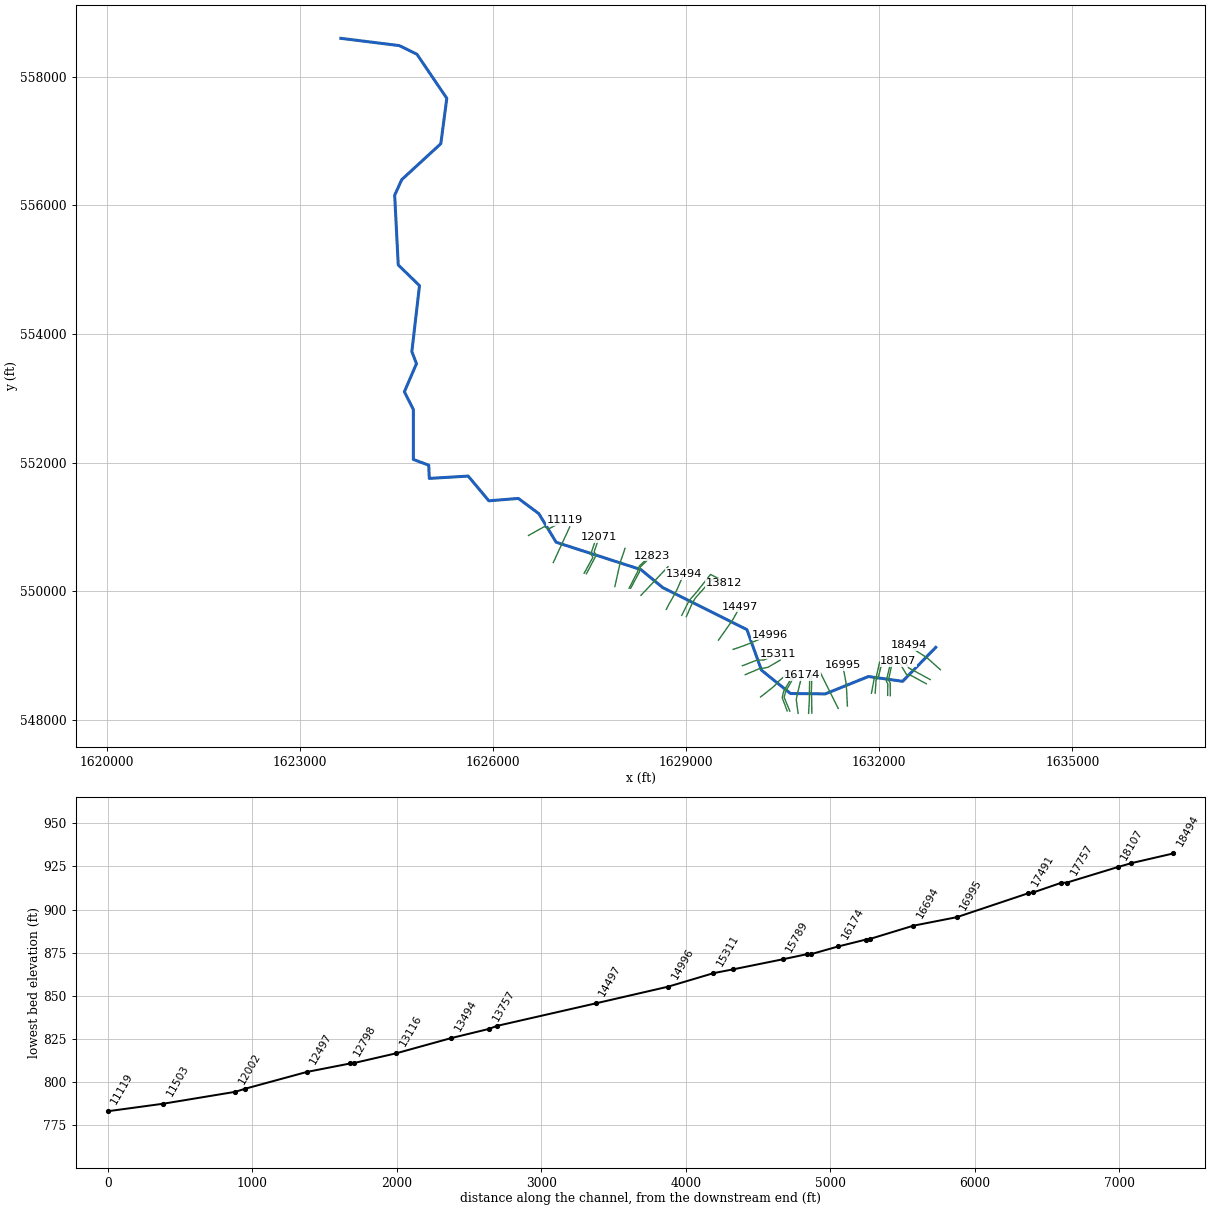
--- BoggsRn.prj (project) ---

Proj Title=BoggsRn
Current Plan=p01
Default Exp/Contr=0,0
English Units
Geom File=g01
Flow File=f01
Plan File=p01
BEGIN DESCRIPTION:
---------- MODELED AS PART OF WVEM CTP PROGRAM, 2025----------
Stream Name: Boggs Run
Flood Zone: AFH
Marshall County, WV
HEC-RAS Version: RAS 6.6
Vertical Datum: NAVD88
Projection: NAD 1983 StatePlane West Virginia N FIPS 4701 (US Feet)
Terrain: 1-meter West Virginia FEMA R3 South Central (collected 2018-2019)
Land Use: 2024 NLCD
Hydrologic Method:
Duda et al., "Estimation of magnitude and frequency of floods for rural, unregulated streams in and near Virginia and West Virginia." September 8, 2025.
Additional Model Notes:
None
END DESCRIPTION:
DSS Export Rating Curves= 0
DSS Export Rating Curve Sorted= 0
DSS Export Volume Flow Curves= 0
DXF OffsetX= 0
DXF OffsetY= 0
DXF ScaleX= 0
DXF ScaleY= 0

--- BoggsRn.p01 (plan) ---

Plan Title=Floodplain
Program Version=4.00
Geom File=g01
Flow File=f01
K Sum by GR=0
Std Step Tol=0.01
Critical Tol=0.01
Num of Std Step Trials=20
Max Error Tol=0.3
Flow Tol Ratio=0.001
Split Flow NTrial=30
Split Flow Tol=0.02
Split Flow Ratio=0.02
Log Output Level=0
Friction Slope Method=1
Unsteady Friction Slope Method=2
Unsteady Bridges Friction Slope Method=1
Global Log Level=0
CheckData=False
Run HTab=0
Run UNet=0
Run PostProcess=0
UNET Theta=0
UNET Theta Warmup=0
UNET ZTol=0
UNET ZSATol=0
UNET MxIter=0
UNET MaxInSteps=0
UNET DtIC=0
UNET DtMin=0
UNET MaxCRTS=0
UNET WFStab=0
UNET SFStab=0
UNET WFX=0
UNET SFX=0
UNET DSS MLevel=0
UNET DZMax Abort=0
UNET Convert EG Bridges=0
UNET Use Existing IB Tables=0
UNET Froude Limit=0
UNET Froude Power=0
Write IC File=0
Echo Input=False
Echo Output=False
Write Detailed=0

--- BoggsRn.f01 (steady flow) ---

Flow Title=Flow
Program Version=6.60
Number of Profiles= 1
Profile Names=P100yr
River Rch & RM=BoggsRn,Main            ,18494
     906
River Rch & RM=BoggsRn,Main            ,13757
    1180
River Rch & RM=BoggsRn,Main            ,11084
    1650
River Rch & RM=BoggsRn,Main            ,5340
    1710
Boundary for River Rch & Prof#=BoggsRn,Main            , 1
Up Type= 0
Dn Type= 3
Dn Slope=0.02435
DSS Import GetInterval= 0
DSS Import GetPeak= 0
DSS Import FillOption= 0

--- BoggsRn.g01 (geometry) ---

Geom Title=Geometry
Program Version=6.60

River Reach=BoggsRn         ,Main
Reach XY= 30
     1632877.348      549131.647     1632362.662       548604.05
     1631831.569      548678.463     1631160.656      548408.581
     1630620.892       548414.38     1630170.568      548776.908
     1629944.737      549407.005     1628637.845      550060.102
     1628298.123      550340.133     1626981.723      550765.252
     1626712.481      551210.244     1626395.385      551446.279
     1625936.514      551409.313     1625615.495      551793.568
     1625011.523      551757.208     1625003.127      551963.287
     1624764.439      552051.513     1624764.991      552827.295
     1624624.887      553104.388     1624812.973      553540.858
     1624740.658      553727.694     1624859.635      554753.756
     1624529.418      555074.622      1624474.19      556159.676
     1624584.099      556400.866     1625190.705      556959.065
     1625283.462      557664.703     1624819.678      558349.729
     1624545.888       558483.61     1623638.575      558596.522

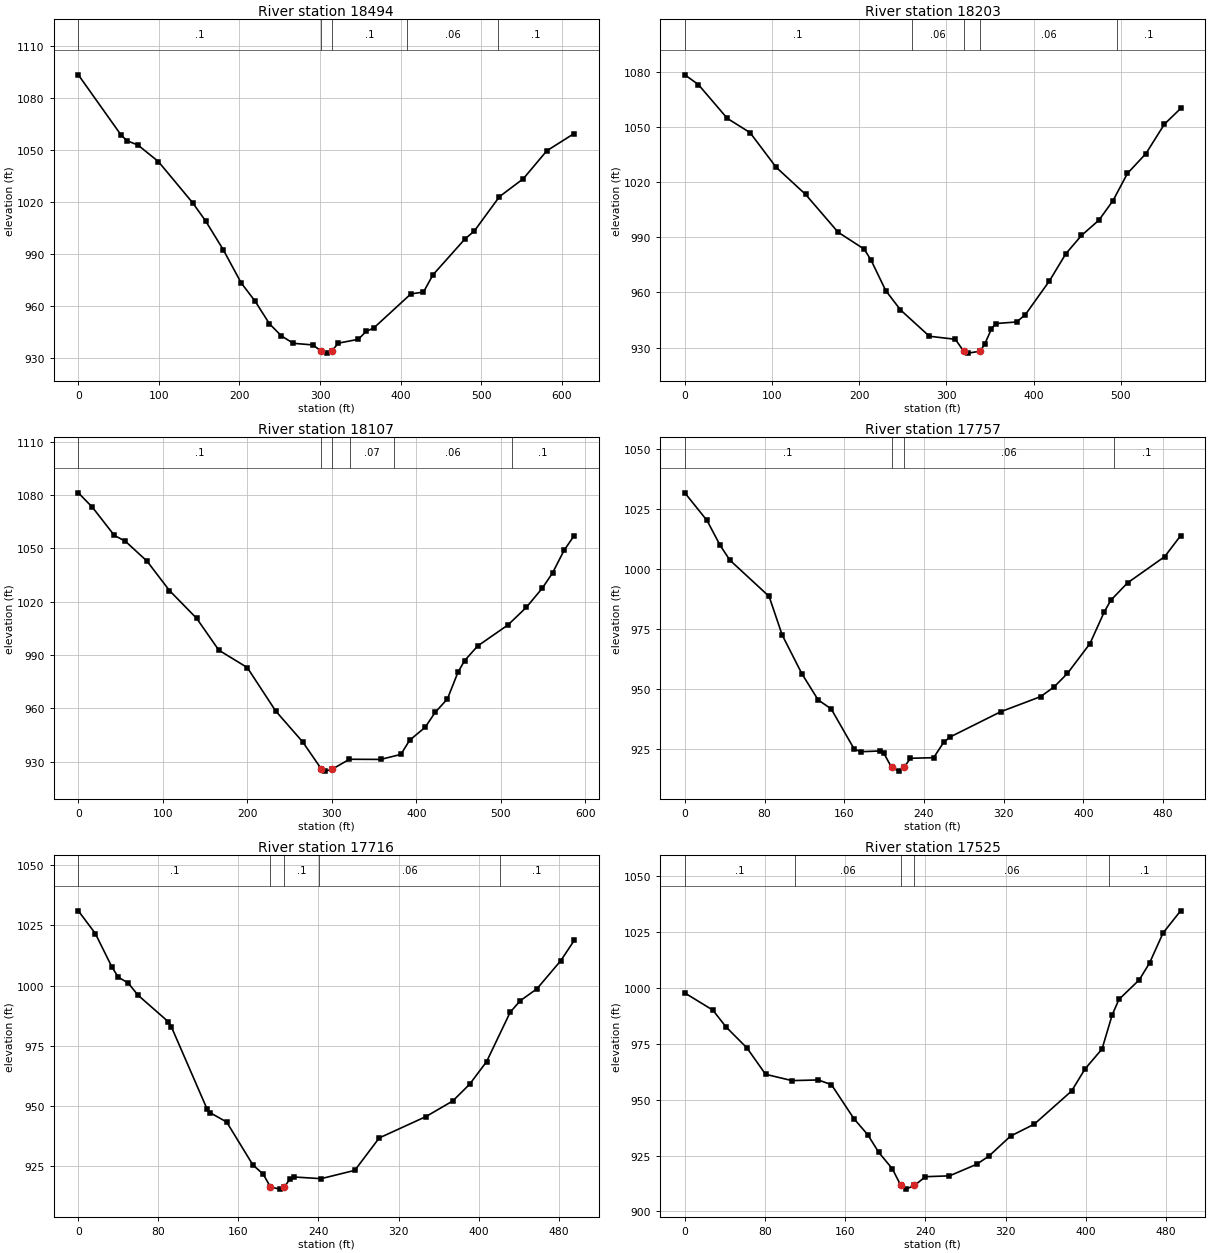
Type RM Length L Ch R = 1 ,18494   ,289.6,291.3,293.1
XS GIS Cut Line= 6
1632948.25496881548785.1609292331632755.70778172548957.394508645
1632673.41857623549014.2362584771632609.85866398549054.287031397
1632537.07337648549103.1261725571632462.99773721549161.291082472
#Sta/Elev= 30
       0 1093.55    53.4 1058.48    60.8 1055.36      74 1052.92    99.3  1043.4
   141.7 1019.64     158    1009   179.9  992.34   202.1  973.18   219.4  962.61
   237.1  949.59   251.9  942.58   266.7  938.26   291.3  937.31  301.36 933.692
   308.6  932.58  314.31933.6918   322.6  938.34   347.5  940.57     357   945.1
   366.5  947.07   412.7  966.85   428.3  967.87     440  977.82   479.5  998.47
   491.4 1003.22   522.6 1023.08   552.3 1033.49   581.3 1049.59   615.3 1059.61
#Mann= 5, -1 ,  0
       0     0.1       0  301.36   0.045       0  314.31     0.1       0
  408.35    0.06       0  521.13     0.1       0
Bank Sta=301.36,314.31
XS Rating Curve= 0 ,0
Exp/Cntr(USF)=0,0
Exp/Cntr=0.3,0.1

Type RM Length L Ch R = 1 ,18203   ,93.6,95.6,97.3
XS GIS Cut Line= 4
1632791.51923427548630.7585695961632519.54009149548779.188827327
1632461.19756244548810.0760485881632349.66037455548967.086090002
#Sta/Elev= 30
       0 1078.69    15.5 1073.41    48.7 1054.95    74.8 1047.17   104.7 1028.31
   138.4 1013.53   175.8  992.86   205.7  983.64   213.5  977.71   230.4  961.04
   247.3  950.51   280.4  936.15   310.2  934.48  319.76 927.984   324.8  926.94
  338.62927.9824   343.7  931.67   351.5  940.01   356.3  943.06   380.4  943.93
   390.4  947.87   418.1  966.34   436.9  981.13   454.8  991.08   474.9  999.48
     491 1010.12   507.5 1024.92   528.7 1035.73   549.9 1051.77   568.5 1060.34
#Mann= 5, -1 ,  0
       0     0.1       0     260    0.06       0  319.76   0.045       0
  338.62    0.06       0  495.86     0.1       0
Bank Sta=319.76,338.62
XS Rating Curve= 0 ,0
Exp/Cntr(USF)=0,0
Exp/Cntr=0.3,0.1

Type RM Length L Ch R = 1 ,18107   ,354.8,350.5,345.1
XS GIS Cut Line= 4
1632730.60277011548565.5522135991632501.52254575548690.817055383
1632421.73055749548711.4085362241632296.46571571548919.897279741
#Sta/Elev= 30
       0 1081.25    16.7  1073.1    42.5 1057.33    55.7 1053.97    81.2 1042.84
   107.8 1026.27   140.1 1010.55   166.2  992.71   199.9  982.91   233.5  958.48
   265.4  941.11  287.72925.7064   292.3  924.62  300.35 925.705   320.8   931.3
   357.8  931.21   381.7  934.04     392     942   410.4  949.29   422.4  957.79
   436.7  965.23   449.4  980.48   457.1   986.8   472.4  995.01   508.5 1006.93
     530 1016.74     549 1027.57   561.1 1036.14   574.8 1048.89   586.7 1057.18
#Mann= 6, -1 ,  0
       0     0.1       0  287.72   0.045       0  300.35     0.1       0
  321.09    0.07       0   373.5    0.06       0   513.5     0.1       0
Bank Sta=287.72,300.35
XS Rating Curve= 0 ,0
Exp/Cntr(USF)=0,0
Exp/Cntr=0.3,0.1

Type RM Length L Ch R = 1 ,17757   ,40.5,41.2,40.8
XS GIS Cut Line= 4
1632171.31393832 548379.702138791632169.47576256548580.670693328
1632143.13112493548622.2141603611632194.36628987548864.128685796
#Sta/Elev= 30
       0 1031.76    22.3 1020.22    35.4  1009.9    45.2 1003.69    84.6  988.55
    97.7  972.46   117.4  956.35   133.8  945.37   146.9  941.63   169.9  924.91
   176.5  923.76   196.2  924.09   199.4  923.37  207.44917.2445   214.7  915.67
  219.99917.2494   226.4  921.03   249.7  921.28   259.8  927.72   266.5  929.97
   316.8  940.41     357  946.75   370.5  950.78   383.9  956.41   406.5  968.85
   420.8  982.03   427.5  986.97   444.2  994.18   481.5 1005.14   497.5 1013.88
#Mann= 4, -1 ,  0
       0     0.1       0  207.44   0.045       0  219.99    0.06       0
  430.17     0.1       0
Bank Sta=207.44,219.99
XS Rating Curve= 0 ,0
Exp/Cntr(USF)=0,0
Exp/Cntr=0.3,0.1

Type RM Length L Ch R = 1 ,17716   ,199.4,190.8,183.1
XS GIS Cut Line= 5
1632130.48274776 548385.013024891632132.39603953548566.647045476
1632112.24212765548599.310281961 1632110.8522027548620.854118791
1632170.61897584548867.565798619
#Sta/Elev= 30
       0 1031.03      17  1021.6    33.4 1007.83    39.9 1003.47    49.8 1001.09
    59.6  996.02    89.7  985.07      93  982.85   128.5  948.89   131.8  947.18
   148.2  943.37   174.4  925.56   184.8  921.68  191.95916.4073   201.1  915.49
  206.01916.4075   211.7  919.86   215.6  920.53   242.6  919.83   276.3  923.29
   300.7  936.74   347.2  945.57   374.2  952.09   391.1  959.06     408  968.43
   431.6  988.95   441.7  993.73   458.3  998.65   482.2 1010.38   495.5 1018.72
#Mann= 5, -1 ,  0
       0     0.1       0  191.95   0.045       0  206.01     0.1       0
  240.02    0.06       0  421.61     0.1       0
Bank Sta=191.95,206.01
XS Rating Curve= 0 ,0
Exp/Cntr(USF)=0,0
Exp/Cntr=0.3,0.1

Type RM Length L Ch R = 1 ,17525   ,34.5,34.1,33.8
XS GIS Cut Line= 4
1631936.41662062548420.0099625361631950.31587019548626.413818618
1631985.75895659548670.1964547561632042.05091733548894.669335276
#Sta/Elev= 30
       0  997.84      28  990.14    41.1  982.64      62  973.21    80.6  961.41
   106.9  958.59   133.2  958.88   146.3  956.76   168.8  941.48   182.5  934.36
   193.5  926.43   206.9  919.18  215.46911.6536   220.8  909.99   229.1911.6547
   240.1  915.56     264  915.93   291.1  921.11   303.3  924.76   324.9  933.72
   348.6  939.08   385.8  953.91   399.3  963.85   416.2  972.74   426.4  988.11
   433.1  994.97   453.4 1003.73   463.6 1011.26   477.1 1024.71   494.6 1034.62
#Mann= 5, -1 ,  0
       0     0.1       0     110    0.06       0  215.46   0.045       0
   229.1    0.06       0   423.2     0.1       0
Bank Sta=215.46,229.1
XS Rating Curve= 0 ,0
Exp/Cntr(USF)=0,0
Exp/Cntr=0.3,0.1

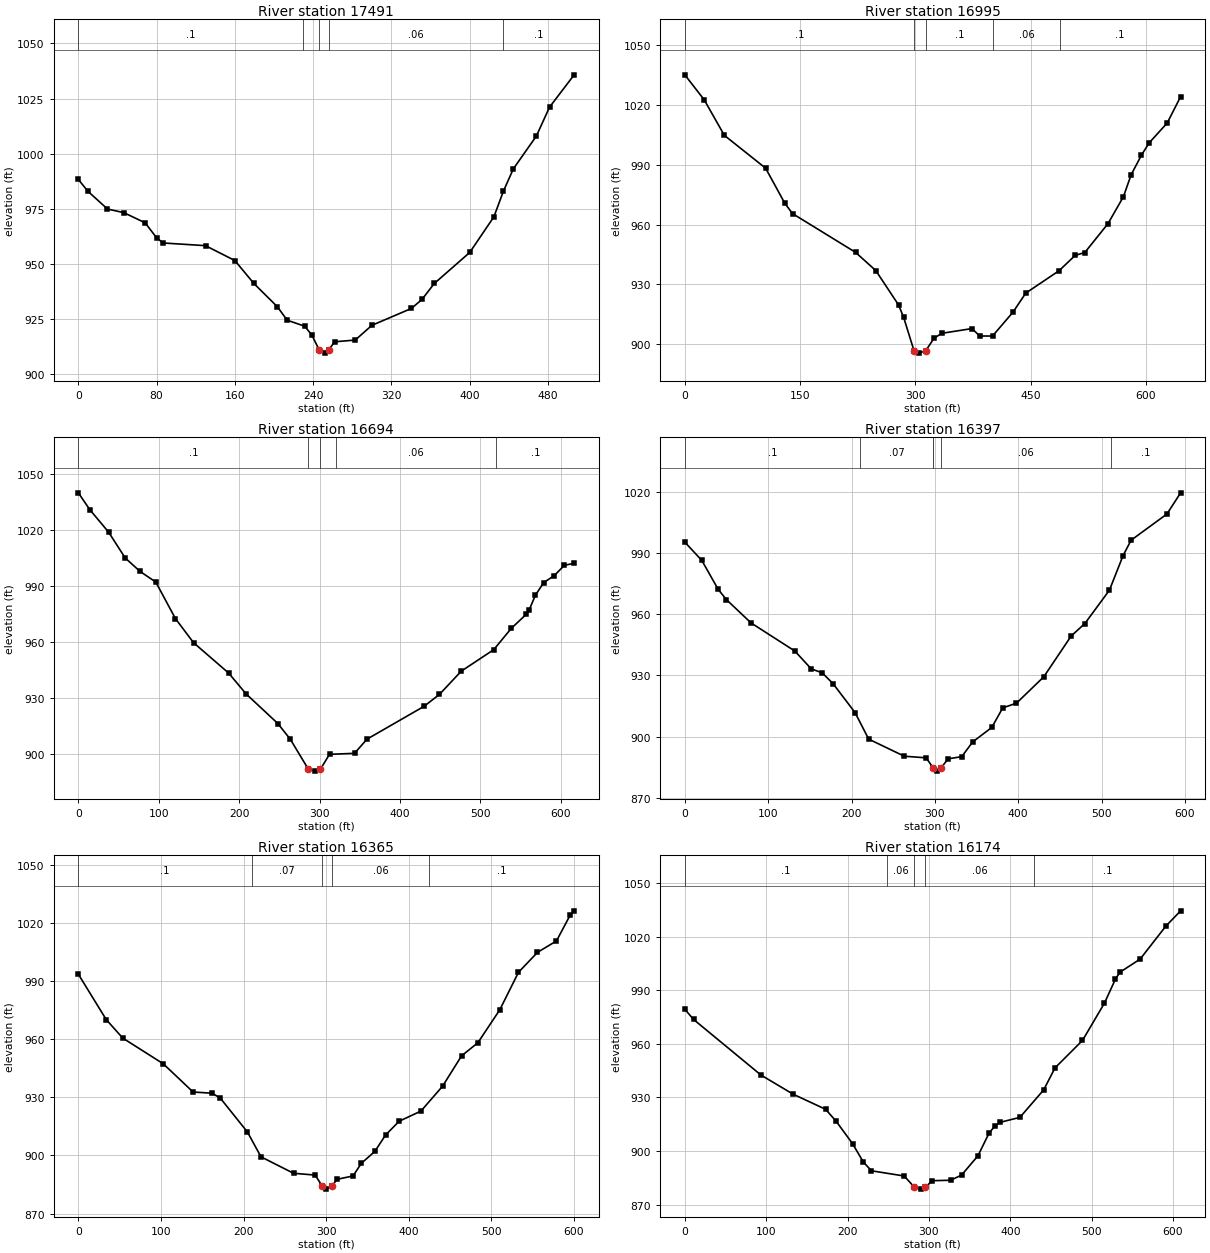
Type RM Length L Ch R = 1 ,17491   ,491.7,496.1,497.6
XS GIS Cut Line= 4
1631878.03977243548418.6200375791631921.12744609548645.872768013
1631956.57053249548684.7906668021632005.21790598548902.313922538
#Sta/Elev= 30
       0  988.32     9.8  982.95    29.8   974.9    46.5  973.26    68.3  968.64
    79.9  961.91    86.6   959.5     130  958.28     160  951.53   179.3  941.19
   203.4  930.58   213.5  924.46   231.3  921.76   238.7  917.74  246.34910.8354
     252  909.53  255.74910.8363   261.9  914.68     283  915.45   300.1  922.15
   340.4  929.79   351.2  933.86   363.9  941.15   400.1  955.21   424.8   971.4
   434.5  983.01   444.6   993.1   468.2 1008.03   481.6  1021.1   506.8 1035.78
#Mann= 5, -1 ,  0
       0     0.1       0     230    0.06       0  246.34   0.045       0
  255.74    0.06       0  433.94     0.1       0
Bank Sta=246.34,255.74
XS Rating Curve= 0 ,0
Exp/Cntr(USF)=0,0
Exp/Cntr=0.3,0.1

Type RM Length L Ch R = 1 ,16995   ,296.8,300.6,302.5
XS GIS Cut Line= 6
1631505.31428514548219.3320083921631492.19193606548475.245538563
1631483.32187505548579.7092403921631468.57059222548665.373767227
1631449.67496072548760.4779077321631429.42893822 548858.68834123
#Sta/Elev= 30
       0    1035    25.2 1022.52    51.5 1004.68   105.2  988.23   130.3  970.57
   140.2   965.5   222.3  946.07   248.6  936.96   278.2  919.75   284.8  913.57
  298.33896.7994   304.5  895.62  313.55896.7967   324.3  903.05   334.3  905.54
   373.8  907.92   383.8  904.19   400.5  904.19   427.1  916.12   443.7  925.66
   487.2  936.92     508  944.56   520.6  946.01   550.8  960.48   570.9     974
   580.9  984.96   594.3  994.76   604.4 1000.95   627.8 1010.85   645.3 1024.09
#Mann= 5, -1 ,  0
       0     0.1       0  298.33   0.045       0  313.55     0.1       0
  401.09    0.06       0  488.01     0.1       0
Bank Sta=298.33,313.55
XS Rating Curve= 0 ,0
Exp/Cntr(USF)=0,0
Exp/Cntr=0.3,0.1

Type RM Length L Ch R = 1 ,16694   ,299,296.9,294.2
XS GIS Cut Line= 2
1631362.64590947548182.4506795271631087.39216017548734.314107914
#Sta/Elev= 30
       0 1039.76    14.3 1030.73    37.7 1018.68    58.3 1004.87    76.7  997.68
    96.4  991.94   120.7  972.43   143.3  959.49   186.9  943.24   208.6  932.08
   248.1   916.2   263.6  907.79  286.12891.7105   294.5  890.69  301.11891.7099
   312.4  899.69   343.5  900.22     359   907.8     430   925.4   449.2  931.81
   476.3  944.24   516.6  955.72   538.6  967.19   556.9  974.61   560.6  976.88
   568.5  984.93   578.9  991.72   591.7  995.33   604.6 1000.93   616.7 1002.02
#Mann= 5, -1 ,  0
       0     0.1       0  286.12   0.045       0  301.11     0.1       0
     320    0.06       0     520     0.1       0
Bank Sta=286.12,301.11
XS Rating Curve= 0 ,0
Exp/Cntr(USF)=0,0
Exp/Cntr=0.3,0.1

Type RM Length L Ch R = 1 ,16397   ,32.8,32.3,32.1
XS GIS Cut Line= 4
1630952.71010214548109.2158783741630950.13616703548327.142383943
1630945.84627519548440.3955285691630952.71010214548703.794887662
#Sta/Elev= 30
       0  995.35    20.4  986.39    40.1  972.15      50  967.14    79.5  955.73
     132  941.97   151.7  933.22   164.8  931.29   177.9  925.95   204.2  911.82
   220.6  898.79   263.3  890.41   289.5  889.62  298.12884.6295   302.7   883.1
  307.36884.6288   315.8  889.13   332.2  890.18   345.3  897.39   368.3  904.53
   381.4   914.1   397.9  916.41   430.7  929.36   463.5  949.34   479.9  955.43
   509.4  971.81   525.8  988.78   535.4  996.29   578.4 1009.14   594.8 1019.51
#Mann= 6, -1 ,  0
       0     0.1       0     210    0.07       0  297.94    0.06       0
  298.12   0.045       0  307.36    0.06       0  511.28     0.1       0
Bank Sta=298.12,307.36
XS Rating Curve= 0 ,0
Exp/Cntr(USF)=0,0
Exp/Cntr=0.3,0.1

Type RM Length L Ch R = 1 ,16365   ,192,191.1,189.1
XS GIS Cut Line= 4
 1630902.0893784  548105.78396491630914.95905393548327.142383943
1630914.95905393548440.3955285691630920.10692414548705.510844399
#Sta/Elev= 30
       0  993.57    33.8  970.14    53.7  960.62   102.8  947.33   138.9  932.77
   161.9  932.13   171.8  929.64   204.7  912.11   221.1  899.31   260.5  890.82
   286.7  889.88  295.39884.0837   299.8  882.63  306.98884.0862     313  887.68
   332.6  889.44   342.5  895.91   358.9   902.1     372   910.6   388.4  917.69
   414.7  922.91   440.9  935.75   463.9  951.42   483.6  958.18   510.1  975.14
   532.8  994.55   555.8 1004.85   578.8 1010.74   595.2 1023.94   600.2 1026.29
#Mann= 5, -1 ,  0
       0     0.1       0     210    0.07       0  295.39   0.045       0
  306.98    0.06       0  424.99     0.1       0
Bank Sta=295.39,306.98
XS Rating Curve= 0 ,0
Exp/Cntr(USF)=0,0
Exp/Cntr=0.3,0.1

Type RM Length L Ch R = 1 ,16174   ,187.5,186.9,186
XS GIS Cut Line= 4
1630739.07348841  548105.78396491630710.76020225548321.994513732
 1630733.9256182548430.9577665171630799.98995256548702.936909294
#Sta/Elev= 30
       0  979.36    10.8  973.63    93.6  942.51   133.3  931.75     173  923.35
     186  916.63   206.1  904.14   219.3  893.88   229.4  888.91   269.6     886
  282.22 879.668   289.8  878.65  295.55879.6687     304  883.36   326.7  883.63
   340.1  886.51   360.2  897.28   373.7  909.82   380.7  913.86   387.3  916.02
   411.8  918.82   441.1  934.26   454.9   946.5   488.7  961.89   515.7  982.78
   529.2  996.24   534.7 1000.07   559.6 1007.45     591  1025.8   609.3 1034.45
#Mann= 5, -1 ,  0
       0     0.1       0  248.06    0.06       0  282.22   0.045       0
  295.55    0.06       0  429.46     0.1       0
Bank Sta=282.22,295.55
XS Rating Curve= 0 ,0
Exp/Cntr(USF)=0,0
Exp/Cntr=0.3,0.1

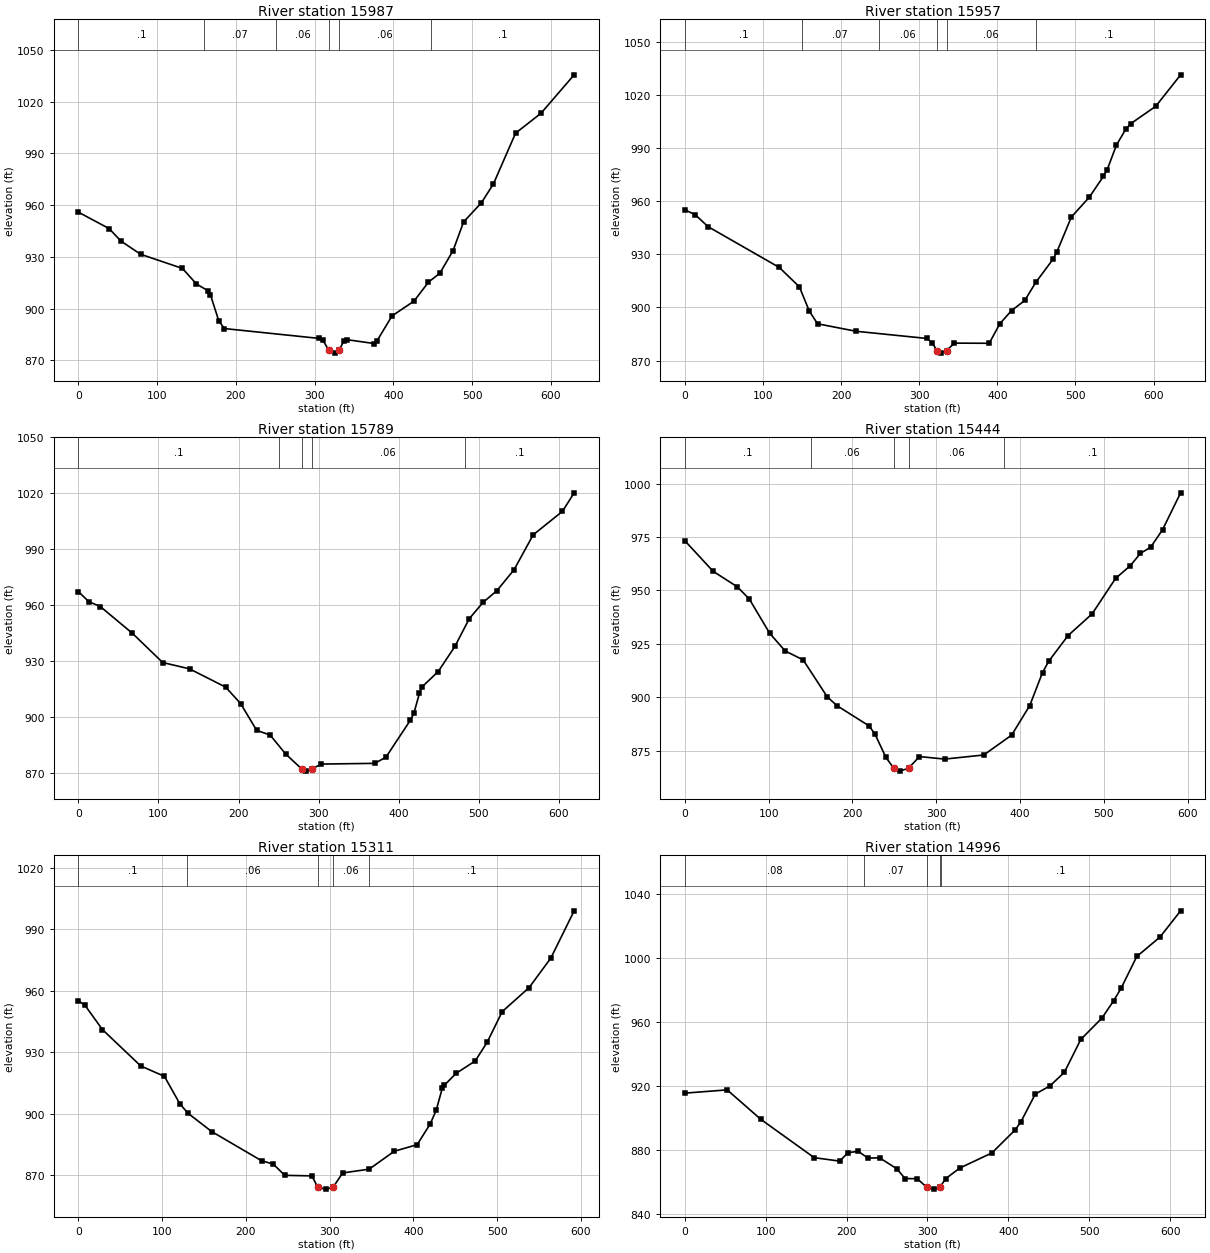
Type RM Length L Ch R = 1 ,15987   ,30.1,29.9,29.5
XS GIS Cut Line= 6
1630610.37673315548141.8190563721630522.86293958548355.455670099
1630537.44857184548414.6561775181630553.75016084548463.560944515
1630572.62568494 548492.732209041630697.89052673548710.658714609
#Sta/Elev= 30
       0  955.92      39  946.42    54.2  939.13      79  931.53   132.2   923.3
     150  914.28   164.1  910.49   167.7  908.05   178.3  892.97   185.4  888.46
   306.1  882.73   310.4  881.77   317.9  875.95     326  874.22  331.16875.9502
   337.3  881.45   340.7  882.04   375.5  879.79   379.4  881.49   398.3  895.81
   426.2  904.37   444.5  915.34     459  920.53   475.8  933.67   489.1  950.24
   511.8  961.38     527  972.28   555.1 1001.67   587.5 1013.28   629.5  1035.5
#Mann= 6, -1 ,  0
       0     0.1       0     160    0.07       0  250.87    0.06       0
   317.9   0.045       0  331.16    0.06       0  448.13     0.1       0
Bank Sta=317.9,331.16
XS Rating Curve= 0 ,0
Exp/Cntr(USF)=0,0
Exp/Cntr=0.3,0.1

Type RM Length L Ch R = 1 ,15957   ,170.8,168.1,166.1
XS GIS Cut Line= 6
1630569.19377147548144.3929914771630492.83369668548348.591843152
1630509.13528568548428.3838314121630529.72676652548481.578490251
  1630549.460269548508.1758196711630673.86713241548719.238498293
#Sta/Elev= 30
       0  955.19    13.2  952.52    29.8   945.7   120.9  922.64   146.6   911.7
   159.4   897.9   169.9  890.77   218.9  886.55   309.8  882.47   316.9  879.96
  322.53875.5677   327.4  874.17  334.95875.5673     345  879.83   389.6  879.74
   403.4  890.91   418.3  898.27   435.1  903.95   449.1  914.12   471.1   927.2
     476  931.18   494.8  951.18   517.7  962.35   535.7  974.11   540.6  977.93
   552.5  991.87   564.5  1000.9     571 1004.03   602.8  1013.8   634.6 1031.58
#Mann= 6, -1 ,  0
       0     0.1       0     150    0.07       0  248.01    0.06       0
  322.53   0.045       0  334.95    0.06       0  449.61     0.1       0
Bank Sta=322.53,334.95
XS Rating Curve= 0 ,0
Exp/Cntr(USF)=0,0
Exp/Cntr=0.3,0.1

Type RM Length L Ch R = 1 ,15789   ,349.9,344.7,339.6
XS GIS Cut Line= 4
1630156.50617628 548360.603540311630360.70502795548522.761451934
1630443.92892969548611.1332238771630624.10438705548764.711351817
#Sta/Elev= 30
       0  967.38    13.1  961.99    27.4  959.37    67.6  944.98   105.3  929.37
   138.8  925.98   183.9  916.19   202.6  907.37   222.6  893.03   239.4  890.53
   258.6  880.46  278.77 872.362   284.1  871.19  291.62872.3615   303.3  874.98
     370  875.35     384  878.68   414.6  898.55   418.9  902.28   425.8  912.93
   428.9  916.26   449.1  924.49   470.1  938.03   487.9  952.81   505.1  961.55
   522.4  967.85   543.9  979.09   567.8   997.8   604.3 1010.36   618.9 1020.28
#Mann= 5, -1 ,  0
       0     0.1       0     250    0.06       0  278.77   0.045       0
  291.62    0.06       0  482.14     0.1       0
Bank Sta=278.77,291.62
XS Rating Curve= 0 ,0
Exp/Cntr(USF)=0,0
Exp/Cntr=0.3,0.1

Type RM Length L Ch R = 1 ,15444   ,134.8,133.4,131.9
XS GIS Cut Line= 4
1629918.84616824548707.2268011361630125.61895502548795.598573079
 1630269.7593209 548821.337924131630460.23051868548932.017133652
#Sta/Elev= 30
       0  973.32    33.8  958.98    62.7   951.7      77  945.97   101.3  929.92
   119.8  921.64   141.2  917.48   169.7  900.31   181.3  896.09   219.7  886.58
   226.7  882.87     240  871.77  249.26866.7289   256.7  865.35  266.98866.7271
     280  872.18     310  870.99   356.7  872.91     390  882.24   411.6  896.09
   426.8  911.53   434.3  916.88   457.3  928.87     486  939.04     514  955.66
   531.6  961.62   543.6  967.38   555.8  970.24     570  978.44   591.6  995.75
#Mann= 5, -1 ,  0
       0     0.1       0     150    0.06       0  249.26   0.045       0
  266.98    0.06       0  381.29     0.1       0
Bank Sta=249.26,266.98
XS Rating Curve= 0 ,0
Exp/Cntr(USF)=0,0
Exp/Cntr=0.3,0.1

Type RM Length L Ch R = 1 ,15311   ,309.9,314.4,317.2
XS GIS Cut Line= 4
1629874.23129308548846.2192968141630099.87960396548933.733090388
1630204.55296491548934.5910687571630429.34329742549032.400602752
#Sta/Elev= 30
       0  955.05     7.7     953    28.8  941.01    74.5  923.27   102.7  918.22
   121.1  904.87   130.8  900.22   159.1  891.29   218.8  877.01   232.7   875.4
   246.3  869.91   278.8  869.64  285.83863.9932   295.8  863.18  303.89 863.989
   315.5  871.08   347.1  872.91   377.1  881.66   404.4  884.87     420  894.99
   427.2  901.75   434.3  912.28   436.8  913.84   450.8  919.64   473.7  925.72
     488  934.86   505.9  949.78   538.1  961.54     564  975.94   591.8  998.97
#Mann= 5, -1 ,  0
       0     0.1       0     130    0.06       0  285.83   0.045       0
  303.89    0.06       0   346.7     0.1       0
Bank Sta=285.83,303.89
XS Rating Curve= 0 ,0
Exp/Cntr(USF)=0,0
Exp/Cntr=0.3,0.1

Type RM Length L Ch R = 1 ,14996   ,494.6,499.9,503.8
XS GIS Cut Line= 6
1629730.03732389 549100.112727151629819.04830073549130.299674645
1629901.80863389549159.2267821431629971.58277255549186.783485562
1630063.70037048549225.699090138 1630298.4315283549328.553215146
#Sta/Elev= 30
       0  915.32    52.4  917.35      94  898.94     160     875   191.4  872.85
     202  878.18   214.4  878.92   226.7   874.7   240.8  874.93     262  868.09
   272.4  861.92   287.4  861.88  299.04 856.512   308.3  855.34  315.33856.5123
   322.6  861.92     340  868.52   379.7  877.97   408.3  892.27   415.5  897.38
   433.3   914.7   451.3  919.81   469.2  928.25   489.6  948.89   515.7  962.21
   530.1  972.96   539.4  980.83   558.8  1000.7   587.4 1012.79     613 1029.23
#Mann= 5, -1 ,  0
       0    0.08       0  221.66    0.07       0  299.04   0.045       0
  315.33    0.07       0  316.68     0.1       0
Bank Sta=299.04,315.33
XS Rating Curve= 0 ,0
Exp/Cntr(USF)=0,0
Exp/Cntr=0.3,0.1

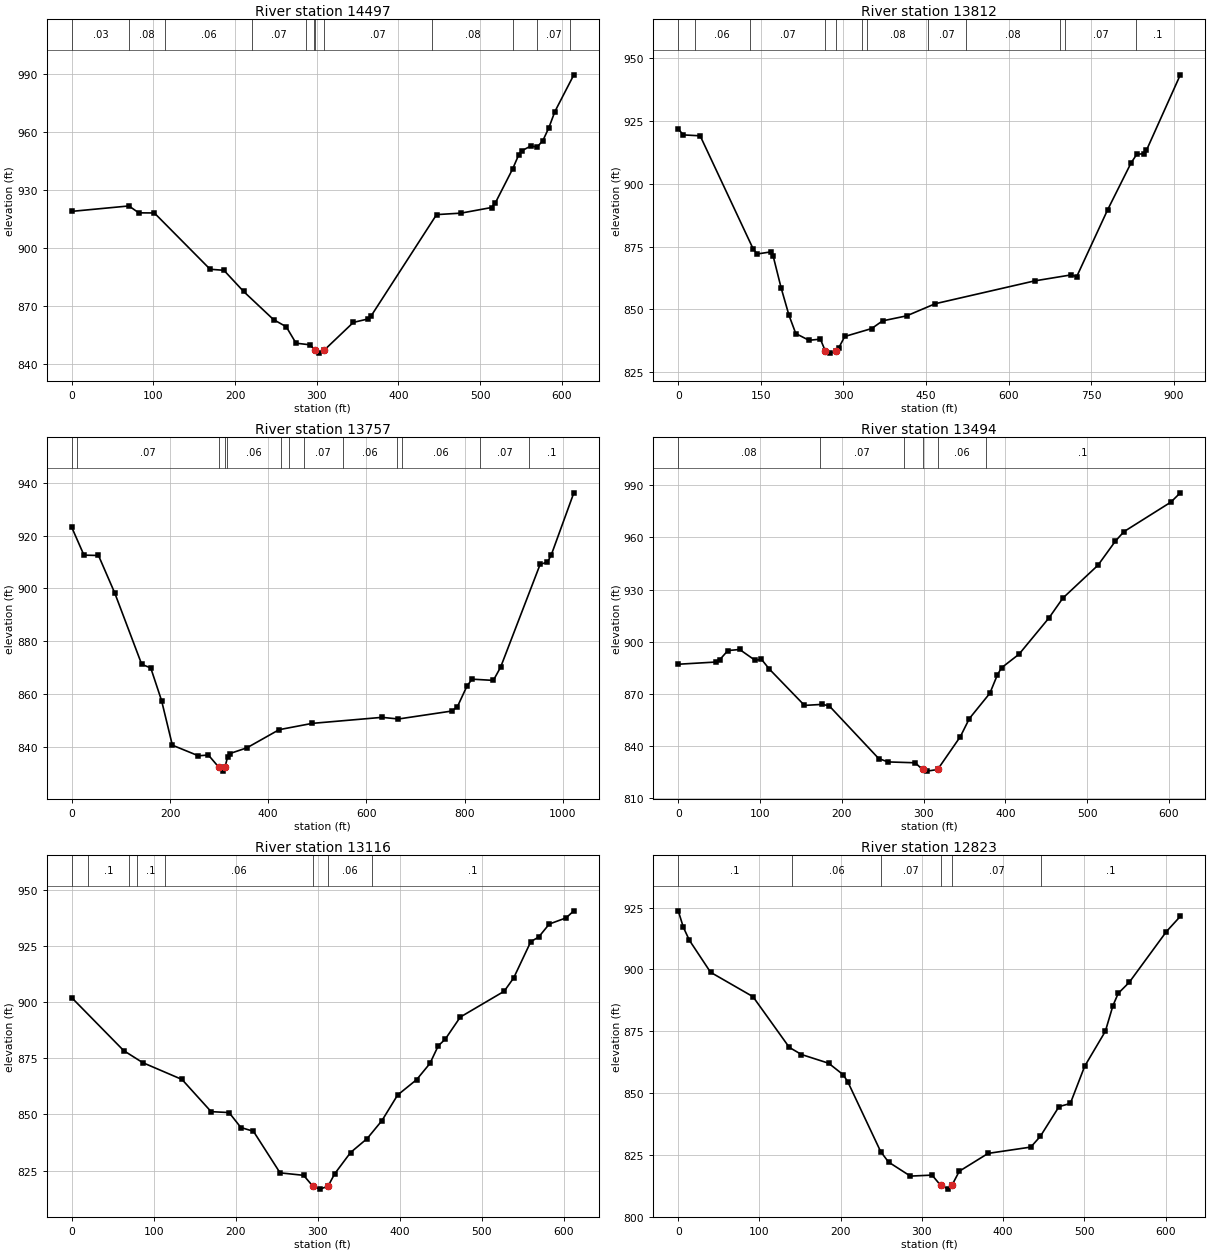
Type RM Length L Ch R = 1 ,14497   ,682.2,684.2,683.6
XS GIS Cut Line= 6
1629502.47216222549243.664933473 1629649.9446363549453.226522222
1629707.49438997549535.0068704781629746.61537471549599.185875982
1629789.05951555549676.8245002331629832.68475638549761.124200389
#Sta/Elev= 30
       0  918.85      70  921.65      82  918.09   101.1  918.03   169.4  888.98
   186.3  888.43   210.4  877.52   247.1  862.98   262.6  859.31   274.6  850.82
   291.8  849.98  298.14 847.071   302.7  845.69  308.72847.0672   344.8  861.55
   362.6  863.31   366.4  864.77   446.7  917.18   476.6  917.94     514  920.84
   518.8  923.35   539.9  940.79   547.3  948.03     551  950.12   562.1  952.58
   569.9  952.06   576.9  955.41   584.2  962.01   591.6  970.38   614.8  989.32
#Mann= 12, -1 ,  0
       0    0.03       0      70    0.08       0  113.75    0.06       0
  221.25    0.07       0  286.25    0.06       0  296.25    0.07       0
  298.14   0.045       0  308.72    0.07       0  441.41    0.08       0
   539.9    0.06       0   569.9    0.07       0   609.9    0.06       0
Bank Sta=298.14,308.72
XS Rating Curve= 0 ,0
Exp/Cntr(USF)=0,0
Exp/Cntr=0.3,0.1

Type RM Length L Ch R = 1 ,13812   ,56.8,54.9,53.2
XS GIS Cut Line= 5
1629003.38324917549608.9620663051629096.04491296549820.024744926
1629144.09170159549898.9587548181629402.34319047550188.955443331
1629591.95640988550124.607065702
#Sta/Elev= 30
       0   921.9     9.3  919.54    39.8  919.18   136.5  873.91   143.7  872.12
   168.8  872.97   172.4  871.23   186.7  858.68   201.1  847.66   213.4  840.42
   237.3  837.74   258.1  838.18  266.83 833.583   276.2  832.62  286.08 833.582
   291.1  834.59   302.3  839.25   351.2  842.41   370.9  845.47   414.6  847.46
   466.6   852.3   646.9  861.39     713  863.77   723.4  863.09   779.4  889.64
   822.1  908.38   832.5  911.84   846.4  912.05   850.1  913.45   911.5  943.47
#Mann= 12, -1 ,  0
       0    0.08       0      30    0.06       0     130    0.07       0
  266.83   0.045       0  286.08    0.07       0  332.91    0.06       0
  342.91    0.08       0  452.91    0.07       0  522.91    0.08       0
  692.91    0.06       0  702.91    0.07       0  831.23     0.1       0
Bank Sta=266.83,286.08
XS Rating Curve= 0 ,0
Exp/Cntr(USF)=0,0
Exp/Cntr=0.3,0.1

Type RM Length L Ch R = 1 ,13757   ,260.9,263.1,263.5
XS GIS Cut Line= 5
 1628932.1710446549629.5535471461629046.28216759549857.775793135
1629162.96722569549990.7624402341629379.17777452550264.457539748
1629594.53034499550155.494286964
#Sta/Elev= 30
       0  923.11    24.8  912.61    54.4  912.48    87.4  898.33   142.4  871.29
   160.8  869.93   182.8  857.59   204.8   840.7   257.8  836.68   278.1  836.97
  299.31832.3715   308.2  830.88  311.85832.3721   317.4  836.32   322.1  837.54
   356.7  839.71   422.1  846.56   489.5  848.95   631.6  851.23   665.1  850.61
   773.8  853.62   785.2  855.29   804.7  863.09     815  865.68   858.3  865.21
   873.1  870.21   953.6  909.14   968.3  909.96     976  912.57  1022.2  936.19
#Mann= 13, -1 ,  0
       0    0.08       0      10    0.07       0  299.31   0.045       0
  311.85    0.07       0  315.16    0.06       0  425.16    0.08       0
  442.08    0.06       0  472.08    0.07       0  552.08    0.06       0
  662.08    0.08       0  672.08    0.06       0  830.87    0.07       0
  930.87     0.1       0
Bank Sta=299.31,311.85
XS Rating Curve= 0 ,0
Exp/Cntr(USF)=0,0
Exp/Cntr=0.3,0.1

Type RM Length L Ch R = 1 ,13494   ,380.6,378.6,375.4
XS GIS Cut Line= 6
1628692.22509505549722.7837258881628735.47697705549805.966302305
1628816.09689455549947.0575555561628861.81333855550036.108886644
1628891.89858022550105.2987089011628963.53524797550272.821011648
#Sta/Elev= 30
       0  887.01    45.9  888.28    50.8  889.64    60.7  894.88    75.1   895.5
      94  889.28   101.8  889.83   111.4  884.23   154.4  863.33   176.3  863.93
   184.7  863.04   245.1  832.79   256.4  830.83   289.8  830.33  298.72826.4729
   304.4  825.53  317.23 826.473     345  845.37     356  855.75   381.1  870.33
   390.4  881.02   395.4  884.99   416.8  892.81   453.4  913.66   470.4  925.07
   513.3  943.96   534.7  957.88   545.1  963.29   602.4  980.24     614  985.61
#Mann= 6, -1 ,  0
       0    0.08       0  173.76    0.07       0  276.26    0.06       0
  298.72   0.045       0  317.23    0.06       0  376.36     0.1       0
Bank Sta=298.72,317.23
XS Rating Curve= 0 ,0
Exp/Cntr(USF)=0,0
Exp/Cntr=0.3,0.1

Type RM Length L Ch R = 1 ,13116   ,289,293.1,296.9
XS GIS Cut Line= 6
1628298.60504883  549941.15912031628363.89592875550008.441466057
1628423.94042807550072.0886484621628475.40686059550126.643001297
1628655.53871816550317.584876636  1628719.939508 550385.71958288
#Sta/Elev= 30
       0  901.88    63.3  878.37    86.5  873.02   134.5  865.52     170  851.21
   191.9  850.81   206.3  844.15   221.6  842.49   254.1     824   282.8   822.9
  294.18818.0279   302.8  816.76  312.55818.0278   320.8  823.61   340.1  833.04
   360.4  839.26   378.4  847.24   397.5   858.6   420.7  865.45   436.9  872.63
   447.1   880.5   455.5  883.38     474  893.28   527.5  904.75   539.1  910.68
     560  926.83   569.6  928.86   582.5  934.64     603  937.38   612.5  940.52
#Mann= 8, -1 ,  0
       0    0.06       0      20     0.1       0      70    0.06       0
      80     0.1       0  113.75    0.06       0  294.18   0.045       0
  312.55    0.06       0  366.25     0.1       0
Bank Sta=294.18,312.55
XS Rating Curve= 0 ,0
Exp/Cntr(USF)=0,0
Exp/Cntr=0.3,0.1

Type RM Length L Ch R = 1 ,12823   ,25.5,25,24
XS GIS Cut Line= 4
1628138.54105384550049.9629476531628274.10163605550301.350609589
1628289.54524668550381.1425978481628469.72070404550556.170184998
#Sta/Elev= 30
       0   923.7     6.3  917.03    13.7   911.8    39.8  898.84      92  888.97
   136.7  868.46   151.7  865.57   185.2  862.03   203.2  857.36   208.9  854.41
   249.2   826.3   258.9  822.05   285.8  816.37   312.5  816.77  323.14812.5872
   332.6   811.1  336.82812.5867     346  818.34   381.5  825.56     434  828.11
   445.7  832.42   468.8  844.49   482.7  845.75   500.4  860.84   525.8  874.95
   535.2  885.37   541.6  890.28   555.3   894.8     601  915.31   618.1  921.46
#Mann= 6, -1 ,  0
       0     0.1       0     140    0.06       0     250    0.07       0
  323.14   0.045       0  336.82    0.07       0  446.88     0.1       0
Bank Sta=323.14,336.82
XS Rating Curve= 0 ,0
Exp/Cntr(USF)=0,0
Exp/Cntr=0.3,0.1

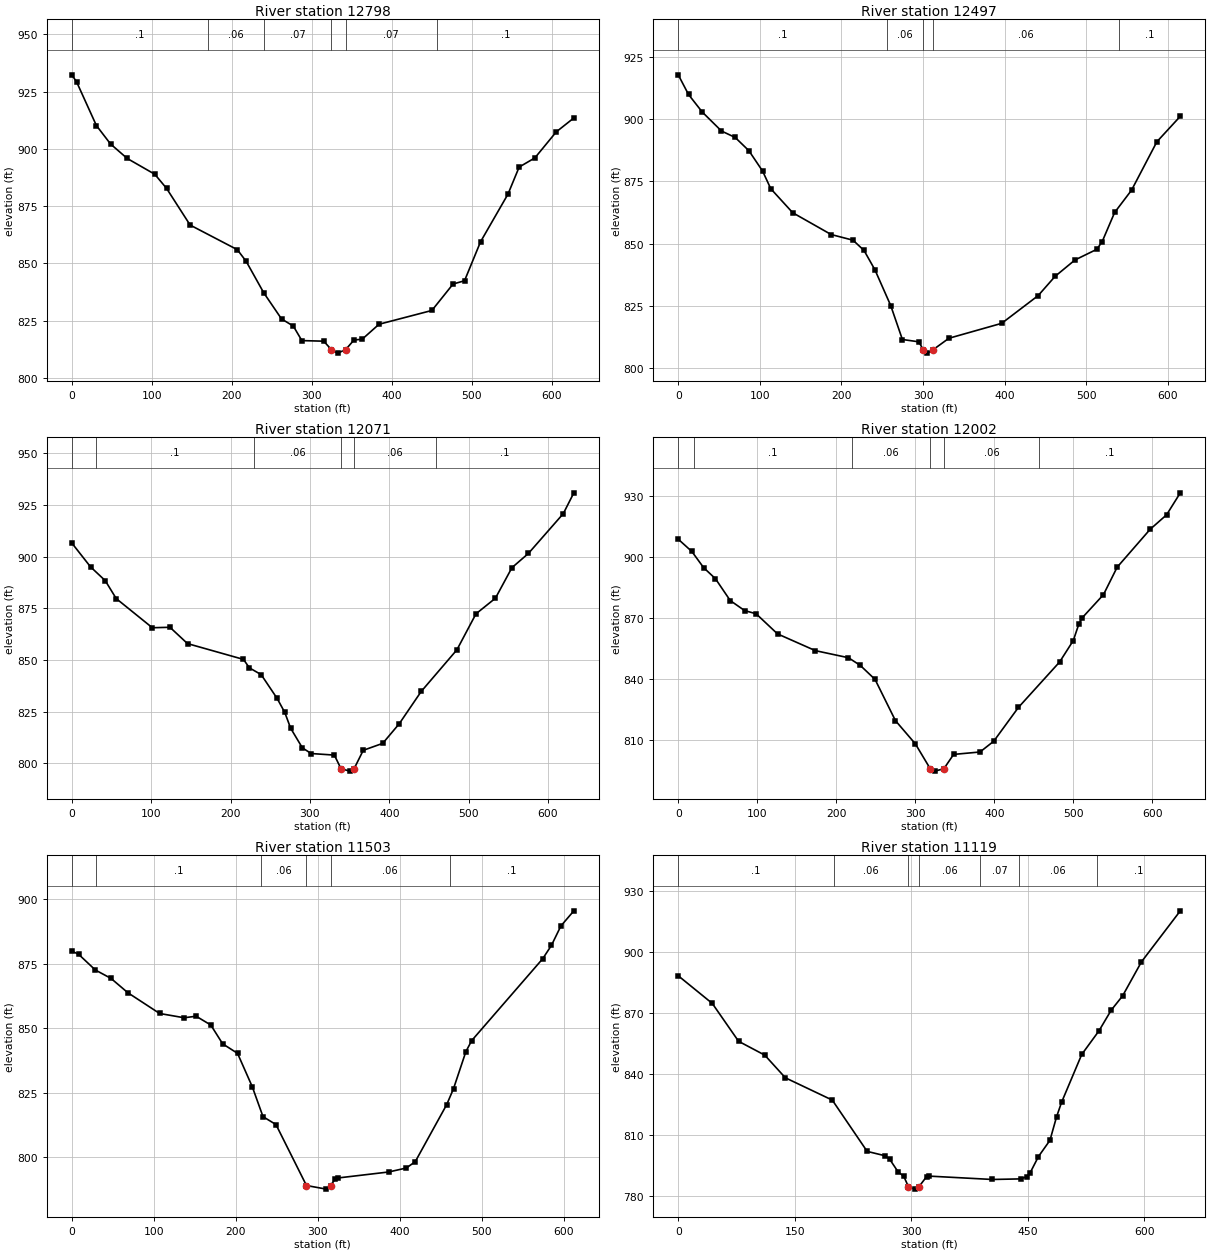
Type RM Length L Ch R = 1 ,12798   ,300.2,300.9,301.9
XS GIS Cut Line= 4
 1628115.3756379 550051.678904391628244.07239315550303.066566325
1628271.52770094550393.1542950051628453.41911504550566.465925419
#Sta/Elev= 30
       0   932.3       6  929.25    30.8  910.17    48.5  902.12    69.3  895.82
   103.8  888.92   118.5  882.77     148  866.75     207  856.01   218.1  850.91
     240  837.22   262.3  825.79     277  822.68   287.7  816.34   315.1  816.08
  324.76812.3356   332.3  810.87  342.31 812.337   352.9  816.61   363.1  816.93
   384.2  823.47   450.3  829.49   476.8  841.03   491.1  842.44   511.1  859.43
   545.5  880.29   559.4  892.05   579.1  896.06   605.8   907.4   627.8  913.48
#Mann= 6, -1 ,  0
       0     0.1       0     170    0.06       0     240    0.07       0
  324.76   0.045       0  342.31    0.07       0  456.59     0.1       0
Bank Sta=324.76,342.31
XS Rating Curve= 0 ,0
Exp/Cntr(USF)=0,0
Exp/Cntr=0.3,0.1

Type RM Length L Ch R = 1 ,12497   ,414.5,425.8,426.2
XS GIS Cut Line= 6
1627893.61579989550075.9637938141627948.94705406550326.161456138
1627970.94930664550423.7114578931627991.55261189550495.971483976
1628021.06042689550579.0631813111628050.73097122550670.086949393
#Sta/Elev= 30
       0  917.92    12.6  910.01    29.4  902.96      53  895.31    69.8  892.72
    86.6  887.39   103.4  879.18   113.4   872.1   140.3  862.43   187.4  853.66
   214.2  851.38   227.7  847.25   241.1  839.43   260.4  825.08   274.7  811.42
   294.9  810.49  300.26 807.274     305  805.94  312.17 807.275   331.7  811.92
   396.4  817.93   441.1  829.09   461.8  836.82   486.2  843.42     513  847.72
   519.6  850.85   534.8  862.53   555.5  871.49   586.6     891   615.3  901.24
#Mann= 5, -1 ,  0
       0     0.1       0  256.24    0.06       0  300.26   0.045       0
  312.17    0.06       0  539.56     0.1       0
Bank Sta=300.26,312.17
XS Rating Curve= 0 ,0
Exp/Cntr(USF)=0,0
Exp/Cntr=0.3,0.1

Type RM Length L Ch R = 1 ,12071   ,67.8,68.6,70.2
XS GIS Cut Line= 4
1627451.33679674550274.0697757981627603.32310807550563.079014893
1627572.25217983550617.1316636021627650.34424047550847.861468677
#Sta/Elev= 30
       0  906.57    23.6  895.04    42.2  888.34      56  879.68   101.5  865.58
   123.7   865.8   145.8  857.91   216.3  850.27   223.8  846.17   238.6  842.91
   258.6  831.46   268.3  824.66   275.7  817.01   290.5   807.5   301.6  804.75
   330.8  803.99  339.18 797.392   350.3  796.24  355.66797.3932   367.2  806.31
   391.7  809.66   412.5  819.13   440.2  834.76   485.2  854.92   509.2   872.3
   533.7  879.86   554.5  894.62   575.3  901.53   619.2  920.76   632.5  930.82
#Mann= 6, -1 ,  0
       0    0.07       0      30     0.1       0     230    0.06       0
  339.18   0.045       0  355.66    0.06       0  458.88     0.1       0
Bank Sta=339.18,355.66
XS Rating Curve= 0 ,0
Exp/Cntr(USF)=0,0
Exp/Cntr=0.3,0.1

Type RM Length L Ch R = 1 ,12002   ,502.8,498.8,487.6
XS GIS Cut Line= 4
1627416.99055127550283.1950995731627552.61369613550531.507525621
1627520.61546368550586.3335421931627614.81385457550859.304391404
#Sta/Elev= 30
       0  908.61    17.2  902.57    32.1  894.62    47.1  889.15    65.8   878.4
      84  873.47    98.5  871.91   125.6     862   173.5  853.75   215.3  850.27
   230.3  846.49     249  839.59   274.8  819.29     300  807.86  318.88 795.583
   324.4  794.44     336795.5834   348.4  802.67   381.8  803.86   399.2  809.18
   430.4  825.81   482.5  848.17   499.8  858.72   506.8  866.81   510.9  869.84
     538  881.33   555.3  894.83     597  913.47   617.8   920.6   635.2  931.44
#Mann= 6, -1 ,  0
       0    0.07       0      20     0.1       0     220    0.06       0
  318.88   0.045       0     336    0.06       0  456.42     0.1       0
Bank Sta=318.88,336
XS Rating Curve= 0 ,0
Exp/Cntr(USF)=0,0
Exp/Cntr=0.3,0.1

Type RM Length L Ch R = 1 ,11503   ,397.4,384.3,373.3
XS GIS Cut Line= 6
1626937.11935331550449.3672464791626976.40536398  550534.4887954
1627013.07261348550613.9354868981627044.50234064550682.032135472
1627117.83683963550840.9255184831627193.79108405551005.493102729
#Sta/Elev= 30
       0  879.88     8.3  878.64    28.7  872.55    47.9  869.27    68.5   863.7
   107.2  855.67   137.1  854.01   151.7  854.61   169.6   851.2   184.1  843.89
   202.2  840.22   220.2  827.26   233.3  815.65   249.1  812.59  286.32 788.938
   310.6  787.54  315.78788.9391   321.4  791.49   324.8  791.87   386.6  794.19
   408.1  795.73     419  798.18   457.4  820.33   465.7   826.5   480.8  840.89
   487.9  845.16   574.5   876.9   585.2  882.11   596.7  889.62   612.5  895.49
#Mann= 6, -1 ,  0
       0    0.07       0      30     0.1       0  231.25    0.06       0
  286.32   0.045       0  315.78    0.06       0  461.25     0.1       0
Bank Sta=286.32,315.78
XS Rating Curve= 0 ,0
Exp/Cntr(USF)=0,0
Exp/Cntr=0.3,0.1

Type RM Length L Ch R = 1 ,11119   ,33.9,34.7,31.1
XS GIS Cut Line= 5
1626552.55540947550870.4463910491626799.25659517551009.030135256
 1626827.4757235550990.561973508 1626865.4885014550972.314162806
1627119.66489449551106.652566532
#Sta/Elev= 30
       0  888.41    43.8  874.78    77.7  856.09   111.4  849.26   137.9  838.09
   198.3  827.09   243.2  801.79   265.8  799.68     272  798.02     283  791.71
   290.3  789.51  296.27784.4316   304.8  783.18  309.94 784.426   319.7  789.35
   323.4  789.59   404.3  787.94   440.9  788.23   448.8  789.34   452.6  790.95
   463.7  799.25   478.5  807.26     487  818.84   493.4  825.96   519.4   849.6
   541.6  861.25   557.4  871.48     572  878.49   596.3  895.29   646.3  920.44
#Mann= 7, -1 ,  0
       0     0.1       0     200    0.06       0  296.27   0.045       0
  309.94    0.06       0  388.85    0.07       0  438.85    0.06       0
  538.85     0.1       0
Bank Sta=296.27,309.94
XS Rating Curve= 0 ,0
Exp/Cntr(USF)=0,0
Exp/Cntr=0.3,0.1