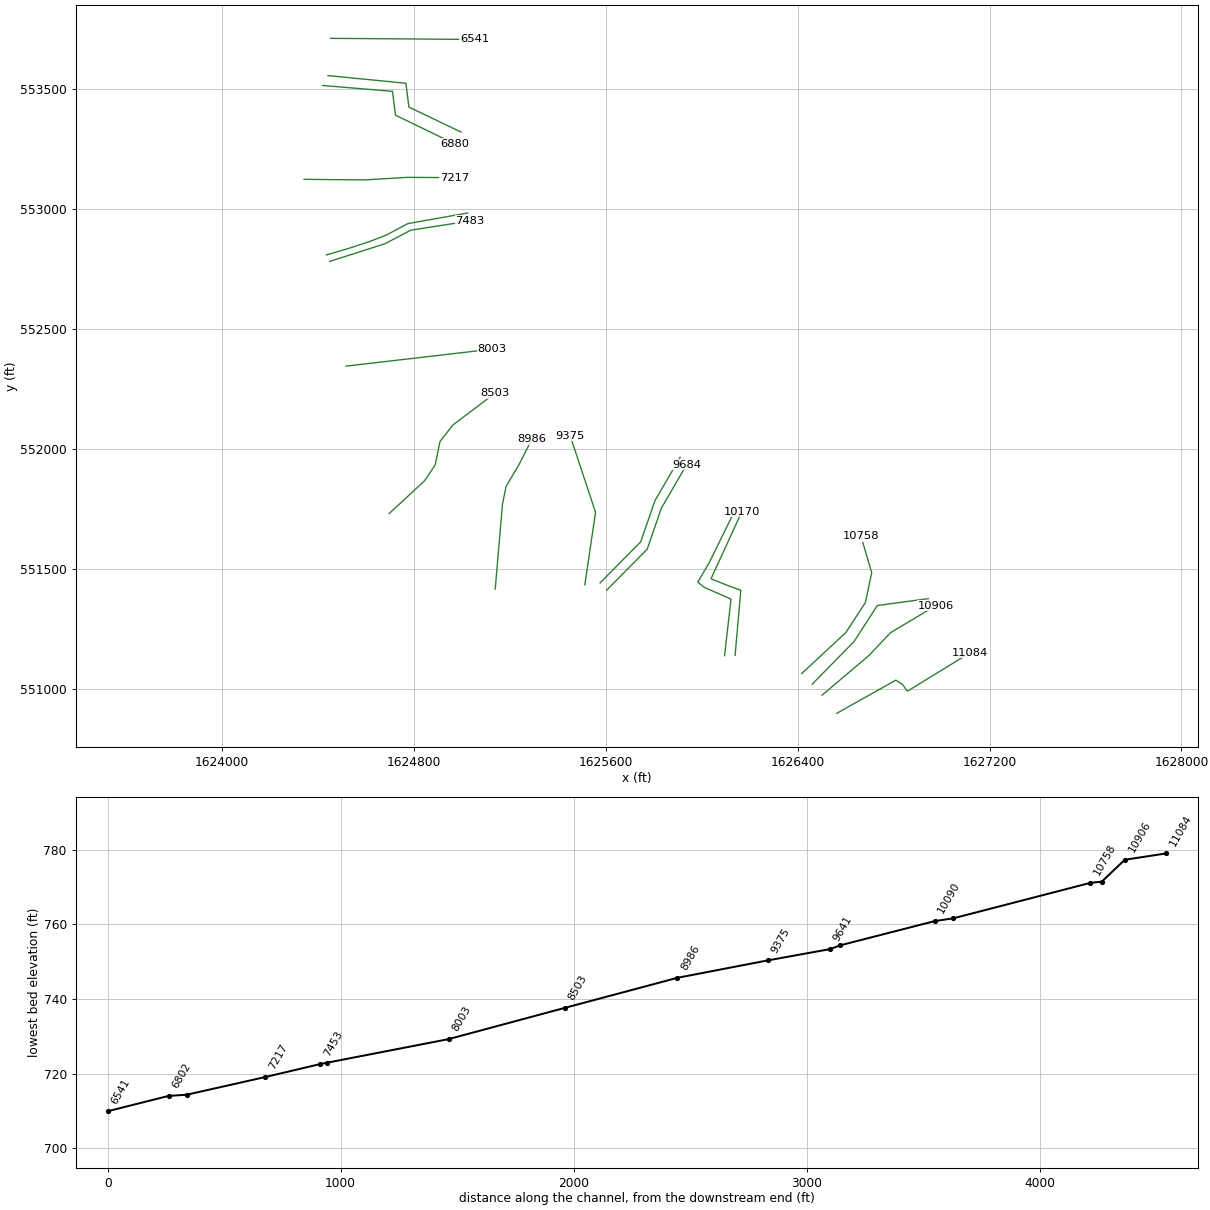
HEC-RAS study BoggsRn.prj: BoggsRn

--- BoggsRn.g01 (geometry) --- (continued)

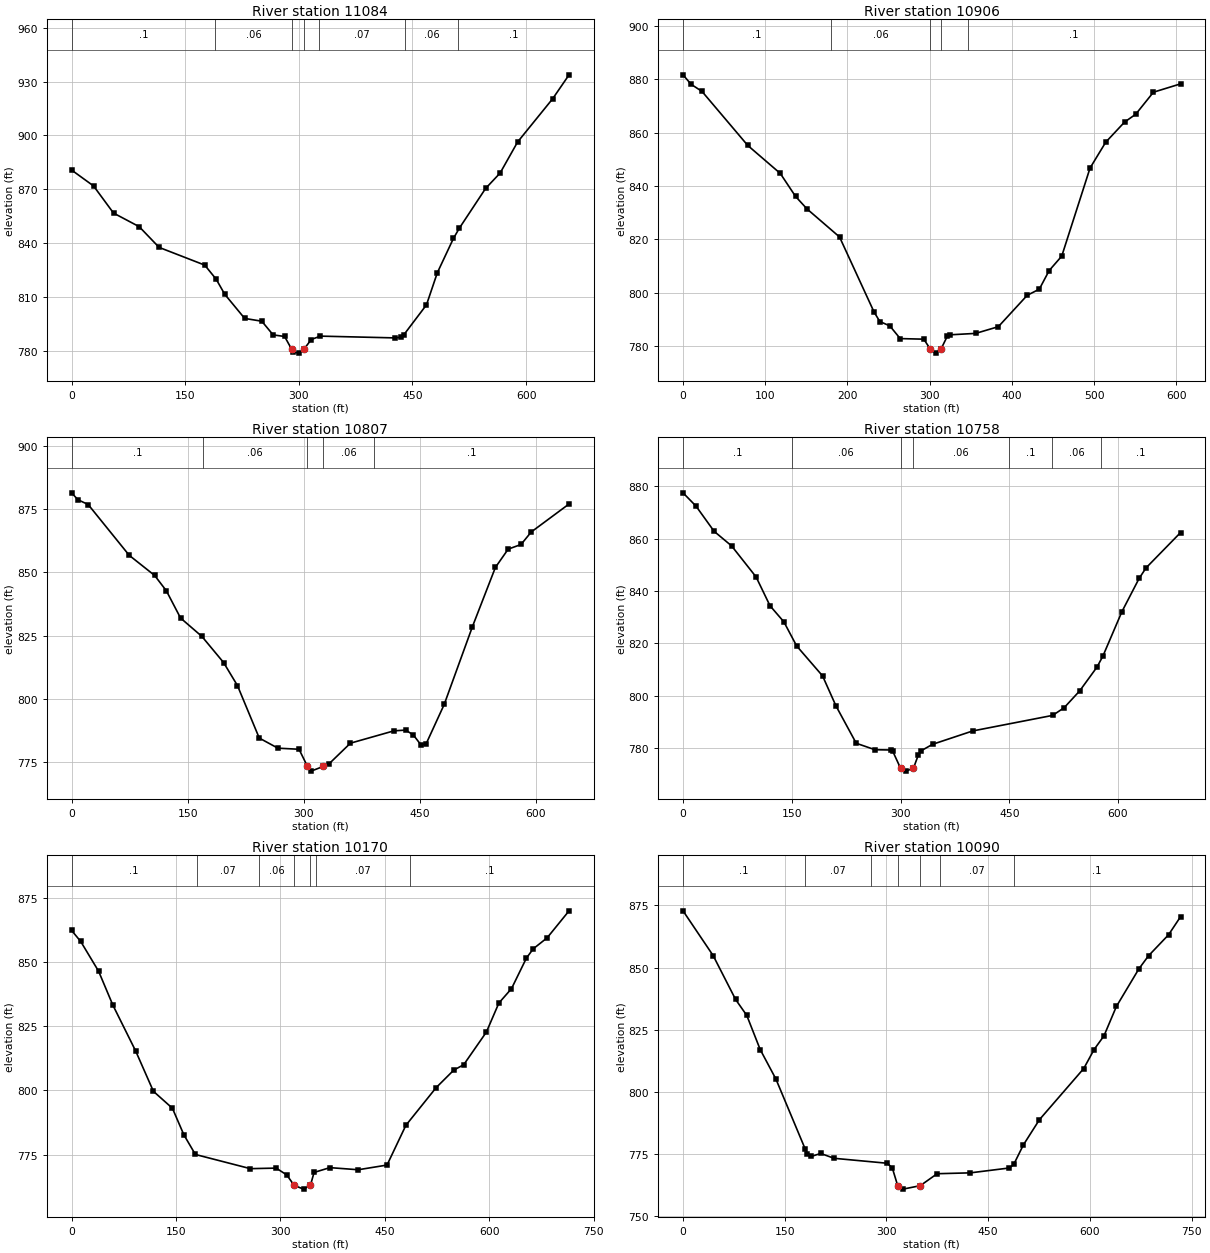
Type RM Length L Ch R = 1 ,11084   ,163,178.1,185.3
XS GIS Cut Line= 5
1626562.11122948550896.4050240141626808.81241518551034.988768221
1626837.03154351551016.5206064731626856.91438015550988.872085487
 1627117.8055663551148.726702841
#Sta/Elev= 30
       0  880.81    29.1  871.93    55.4  856.88    89.3  849.32   115.6   837.8
   175.8  827.96   190.9  820.12   202.2  811.76   228.5  798.33   251.1  796.78
   266.1  789.17   281.2   788.3  290.48781.2512   292.9  779.52   300.7  779.04
  306.84781.2468   316.4  786.61   328.5  788.49   427.2   787.5   434.9  787.91
   438.7  789.29   468.5  805.88   482.8   823.7   504.1  842.81   511.8  848.43
   546.5  870.55   565.7  879.13   588.8   896.4     635  920.39   656.7  933.71
#Mann= 7, -1 ,  0
       0     0.1       0     190    0.06       0  290.48   0.045       0
  306.84    0.06       0  326.69    0.07       0  440.74    0.06       0
  510.74     0.1       0
Bank Sta=290.48,306.84
XS Rating Curve= 0 ,0
Exp/Cntr(USF)=0,0
Exp/Cntr=0.3,0.1

Type RM Length L Ch R = 1 ,10906   ,96.3,99,100.9
XS GIS Cut Line= 4
1626501.19614434550972.3442858821626696.81521233 551137.93411098
1626786.90294101 551233.169709871626973.94222532 551344.70689776
#Sta/Elev= 30
       0  881.68     9.8  878.14    23.1  875.46    78.8  855.19   118.3  844.72
   136.9  836.09   150.9  831.38   190.4  820.89   232.4  792.75   239.4  789.19
   251.6  787.54   264.2  782.79   292.9  782.57  300.83778.8427   307.2  777.34
   313.8778.8456   321.5  783.69   324.3   784.2     356  784.74   383.6  787.26
   418.7  799.02   433.4  801.32   445.4   808.3   460.7  813.71   495.1  846.72
   514.2  856.42   537.1  863.96   550.7  866.91   572.2  875.16   605.2  878.29
#Mann= 5, -1 ,  0
       0     0.1       0     180    0.06       0  300.83   0.045       0
   313.8    0.06       0  346.29     0.1       0
Bank Sta=300.83,313.8
XS Rating Curve= 0 ,0
Exp/Cntr(USF)=0,0
Exp/Cntr=0.3,0.1

Type RM Length L Ch R = 1 ,10807   ,49.5,49.5,49.2
XS GIS Cut Line= 4
1626459.75717748551017.8532237051626635.11901135 551196.74583275
1626731.62686623551346.2153153071626944.25838595551374.929932909
#Sta/Elev= 30
       0  881.42     8.3  878.69    21.5  876.79    74.6  856.71   107.4  848.77
   122.5  842.73   140.9  831.95   168.5  824.67   196.5  814.37   214.4  805.28
   242.6  784.53   266.7  780.53     294   780.1  304.88773.3376   309.6  771.46
  325.47773.3355   333.1  774.43   360.4   782.5   416.7  787.38   431.9  787.67
   441.8  785.73   451.8  781.75   458.4  782.33   481.6  797.79     518  828.46
   547.8  851.95   564.3  859.17   580.9  861.01   594.1  865.95     643  877.02
#Mann= 5, -1 ,  0
       0     0.1       0     170    0.06       0  304.88   0.045       0
  325.47    0.06       0  390.51     0.1       0
Bank Sta=304.88,325.47
XS Rating Curve= 0 ,0
Exp/Cntr(USF)=0,0
Exp/Cntr=0.3,0.1

Type RM Length L Ch R = 1 ,10758   ,572.6,587.6,602.3
XS GIS Cut Line= 5
1626416.87120524551062.9941843621626600.47151452 551233.64831799
1626681.67934363551358.402374298 1626708.2413653551483.086992027
 1626663.2722357551635.787133873
#Sta/Elev= 30
       0  877.48    17.9  872.41    42.9  862.77      67   857.2   100.8  845.33
     120  834.32   139.1  828.18   156.7  818.98   192.5  807.51     211  796.03
   238.9  781.78   264.7  779.31   286.9  779.21   289.4  778.64     300772.2538
   307.4  771.13  317.85772.2539   324.6  777.34   328.5  778.92   344.2  781.38
   399.5  786.48   509.8  792.43   525.7  795.37   547.1  801.79   570.9  810.86
     579  815.02   605.4   832.1   629.1  844.79   638.7  848.82   686.2  862.29
#Mann= 7, -1 ,  0
       0     0.1       0     150    0.06       0     300   0.045       0
  317.85    0.06       0  449.52     0.1       0  509.52    0.06       0
     577     0.1       0
Bank Sta=300,317.85
XS Rating Curve= 0 ,0
Exp/Cntr(USF)=0,0
Exp/Cntr=0.3,0.1

Type RM Length L Ch R = 1 ,10170   ,77,80,80.7
XS GIS Cut Line= 6
1626138.45264632551138.1371649961626162.39024279551409.944712098
1626116.83159143551426.1605032611626083.62782858551439.287572297
1626038.06917722551457.8199050541626166.89608837551738.205484863
#Sta/Elev= 30
       0  862.28    13.2  857.95    38.9  846.37    59.3  833.24    92.2  815.31
   117.6  799.68   144.9  793.09   161.4  782.73   177.9  775.11   256.9  769.59
     294  769.81   309.2  767.14  319.77763.0935   333.3  761.63  343.15 763.095
   348.4  768.12   371.1  769.99   411.8  769.17   453.2  770.99   480.3  786.46
   523.7  801.09     549   807.9   563.4  810.04   595.9  822.71   613.9  834.03
     632  839.61   653.5  851.53   663.4  855.14   683.2  859.38   714.7  869.88
#Mann= 7, -1 ,  0
       0     0.1       0     180    0.07       0     270    0.06       0
  319.77   0.045       0  343.15    0.06       0  351.22    0.07       0
  486.11     0.1       0
Bank Sta=319.77,343.15
XS Rating Curve= 0 ,0
Exp/Cntr(USF)=0,0
Exp/Cntr=0.3,0.1

Type RM Length L Ch R = 1 ,10090   ,413.7,405.7,374.2
XS GIS Cut Line= 6
1626094.43835602551136.5928039331626121.46467462551372.880046584
1626011.04285861551421.5274200721625982.74241295551443.775324457
1626029.96981743551523.9895041091626138.76373643551744.571450893
#Sta/Elev= 30
       0  872.85    44.5  854.82    77.5   837.2      94  830.78   113.8  817.04
     137  805.16     180  777.12   183.2  775.18   188.9  774.02     203  775.23
   222.8  773.28   301.5  771.28   308.7   769.3  316.55762.2745   324.3  760.88
  349.86762.2726   374.7  767.08   423.7  767.43   481.2  769.39   487.6  770.79
   501.8  778.64   525.6  788.85   590.9  809.41   606.1  817.04   620.7  822.55
     639  834.36   672.1  849.47   686.6  854.83   715.9   863.2   733.6  870.48
#Mann= 7, -1 ,  0
       0     0.1       0     180    0.07       0  277.83    0.06       0
  316.55   0.045       0  349.86    0.06       0  378.52    0.07       0
   487.6     0.1       0
Bank Sta=316.55,349.86
XS Rating Curve= 0 ,0
Exp/Cntr(USF)=0,0
Exp/Cntr=0.3,0.1

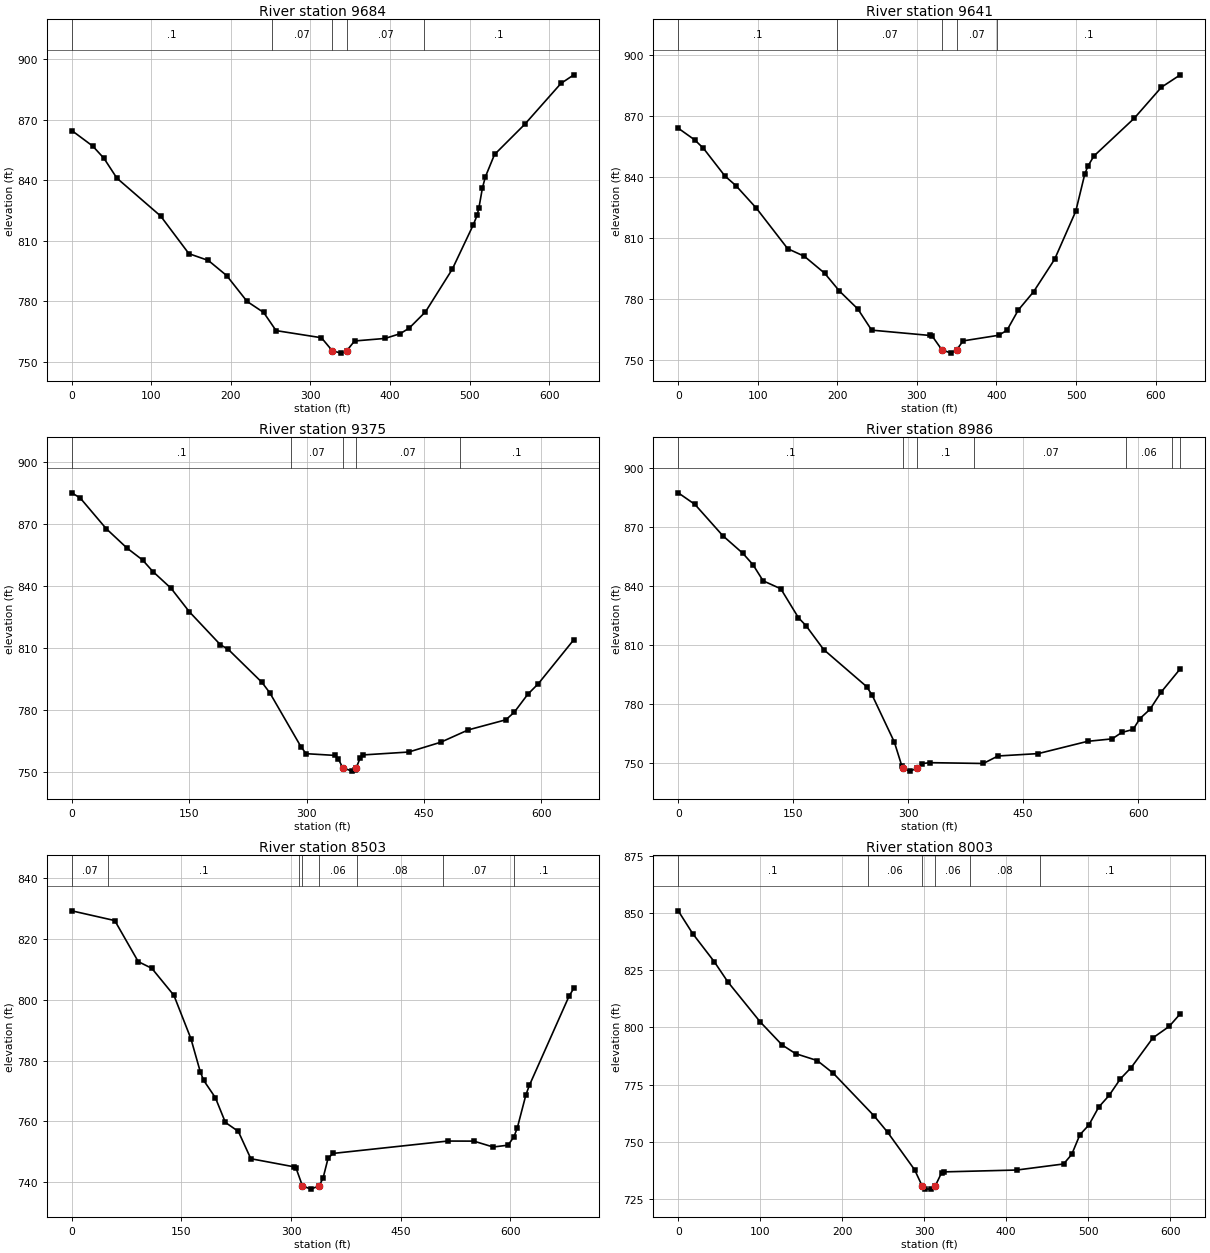
Type RM Length L Ch R = 1 ,9684    ,43.1,43.3,43.1
XS GIS Cut Line= 4
1625602.50157593551409.712536553 1625771.9787845551581.308210229
 1625831.2958075551752.903883905 1625936.1598303551932.973418009
#Sta/Elev= 30
       0  864.59    26.5  856.83    40.5  850.81    56.7  841.02   111.7  822.25
   147.2  803.63   171.7  800.25   194.7  792.77   220.4  779.96   241.2  774.51
   256.8  765.53   313.8     762  327.22 755.674   337.9  754.38  345.85755.6719
   355.5   760.4   393.7  761.65   412.7  763.99   424.1  766.74   444.6  774.82
   478.3  795.93   504.6  817.81   509.4  822.53   511.8  826.33   516.2  836.22
     520  841.75   531.4  852.72   569.4  867.67   614.9  887.91   631.1  892.16
#Mann= 5, -1 ,  0
       0     0.1       0  251.18    0.07       0  327.22   0.045       0
  345.85    0.07       0  442.74     0.1       0
Bank Sta=327.22,345.85
XS Rating Curve= 0 ,0
Exp/Cntr(USF)=0,0
Exp/Cntr=0.3,0.1

Type RM Length L Ch R = 1 ,9641    ,259.4,266.5,270
XS GIS Cut Line= 4
1625575.49114582551440.4302806061625744.96835438551612.025954282
1625804.28537738551783.6216279581625909.14940019551963.691162062
#Sta/Elev= 30
       0  863.85    20.8  858.07    31.7  853.96    58.7  840.36    72.6   835.6
    98.2  824.57   137.6  804.66   158.5  800.94     184  792.63   202.6  783.87
   225.8  775.03   243.1  764.66   316.9  762.03   319.5  761.59  331.27755.0594
   342.7  753.37  349.99755.0586   358.2  759.39   402.8  762.14   413.2  764.58
   427.4  774.51   446.7  783.53   473.1  799.46   499.7  823.08     511  841.28
   514.8  845.08   522.4  850.14   573.2  868.73   607.4  883.98   631.1  890.06
#Mann= 5, -1 ,  0
       0     0.1       0     200    0.07       0  331.27   0.045       0
  349.99    0.07       0  401.18     0.1       0
Bank Sta=331.27,349.99
XS Rating Curve= 0 ,0
Exp/Cntr(USF)=0,0
Exp/Cntr=0.3,0.1

Type RM Length L Ch R = 1 ,9375    ,392.8,388.8,385.6
XS GIS Cut Line= 3
1625511.80882473551432.6144088691625556.55450812551734.986754152
1625450.79198376552053.630257028
#Sta/Elev= 30
       0  885.08    10.8  882.57    43.9  867.77    70.5  858.35    90.4  852.58
   103.6  846.99   126.9  838.84   150.1  827.54   189.9  811.52   199.7  809.37
     243   793.3   252.9  788.31   292.7  762.22   299.3   758.8   336.5  757.95
   340.5   756.3  346.03752.0313   357.8  750.35   361.3  750.66  363.49752.0361
   368.2  756.52   371.6  758.18   430.4  759.59   471.4  764.34   506.5  770.31
   554.5   775.2   565.2  778.82   582.5  787.53     596  792.67   641.4  813.98
#Mann= 5, -1 ,  0
       0     0.1       0     280    0.07       0  346.03   0.045       0
  363.49    0.07       0  495.67     0.1       0
Bank Sta=346.03,363.49
XS Rating Curve= 0 ,0
Exp/Cntr(USF)=0,0
Exp/Cntr=0.3,0.1

Type RM Length L Ch R = 1 ,8986    ,477.6,482.4,480.1
XS GIS Cut Line= 6
1625138.12509197551414.9763700631625146.13196571551508.383991641
1625168.55055605551769.9251352221625183.87171963551843.886601475
1625236.48185064551932.0603096451625290.81540339552039.514491063
#Sta/Elev= 30
       0   887.4    21.8  881.49      58  865.62    84.4  856.54    97.5   850.8
   110.7  842.59   133.8  838.53   156.8  823.79   166.7  819.73   189.7  807.58
   245.7  788.72   252.9  784.41   281.9  760.45   291.8  748.11  293.46747.1038
   301.7  745.67  312.04747.1031   318.2   749.5     328  749.99   397.9  749.56
   417.1  753.38   469.6   754.6     534  760.85     566   762.1   578.6  765.37
   593.3   766.9   602.3  772.47   615.4  777.16   630.1  786.01   654.9  797.81
#Mann= 7, -1 ,  0
       0     0.1       0  293.46   0.045       0  312.04     0.1       0
  386.25    0.07       0  584.46    0.06       0  644.46     0.1       0
  654.46    0.06       0
Bank Sta=293.46,312.04
XS Rating Curve= 0 ,0
Exp/Cntr(USF)=0,0
Exp/Cntr=0.3,0.1

Type RM Length L Ch R = 1 ,8503    ,517.1,500,489.1
XS GIS Cut Line= 6
1624696.14516072551729.9152103071624843.34106055551866.204635888
1624887.76616855551932.2232046431624907.80615473552030.194793478
1624962.25355239552099.4170959741625136.36344039552230.813486725
#Sta/Elev= 30
       0  829.32    58.8  826.11    90.9  812.59   109.5  810.37   139.7  801.47
   162.9  787.23   175.9  776.17   180.5  773.42   196.4  767.76   210.1   759.6
   227.8  756.64   244.9  747.64   303.6  744.99   306.9  744.44  315.49738.6819
     327  737.62  338.33738.6835   343.8  741.33   350.5  747.75   357.2  749.38
   514.2  753.46   549.9  753.44   576.3   751.5   596.7   752.1   604.7  754.84
   609.4  757.83   621.2  768.75   625.9  771.83   680.2  801.23   686.7  803.81
#Mann= 8, -1 ,  0
       0    0.07       0      50     0.1       0  310.25    0.06       0
  315.49   0.045       0  338.33    0.06       0  390.25    0.08       0
  508.32    0.07       0  605.14     0.1       0
Bank Sta=315.49,338.33
XS Rating Curve= 0 ,0
Exp/Cntr(USF)=0,0
Exp/Cntr=0.3,0.1

Type RM Length L Ch R = 1 ,8003    ,516.8,520.4,522.4
XS GIS Cut Line= 6
1624516.22557305552344.4891123921624609.34809022 552355.31783089
1624696.26261455552365.4241098911624770.76049705552374.086822227
1625031.50374196552404.4069715591625124.62593105552415.235690057
#Sta/Elev= 30
       0  851.03    17.6  841.07      44  828.74    60.5  819.93   100.1  802.37
   126.6  792.36   143.1  788.53   169.5   785.5   189.3  779.89   238.9  761.29
   255.4  754.13   288.4  737.68  297.36730.7548   301.6  729.28   308.2  729.22
  313.72730.7595   321.4  736.47   324.7  736.77   413.1  737.58   470.1  740.23
     480   744.4     490  753.03   500.9  757.26     513  765.14   525.6  770.21
   539.4  777.49   552.6  782.44   579.1  795.43   598.9  800.44   612.5  805.99
#Mann= 6, -1 ,  0
       0     0.1       0  231.25    0.06       0  297.36   0.045       0
  313.72    0.06       0  356.25    0.08       0  441.25     0.1       0
Bank Sta=297.36,313.72
XS Rating Curve= 0 ,0
Exp/Cntr(USF)=0,0
Exp/Cntr=0.3,0.1

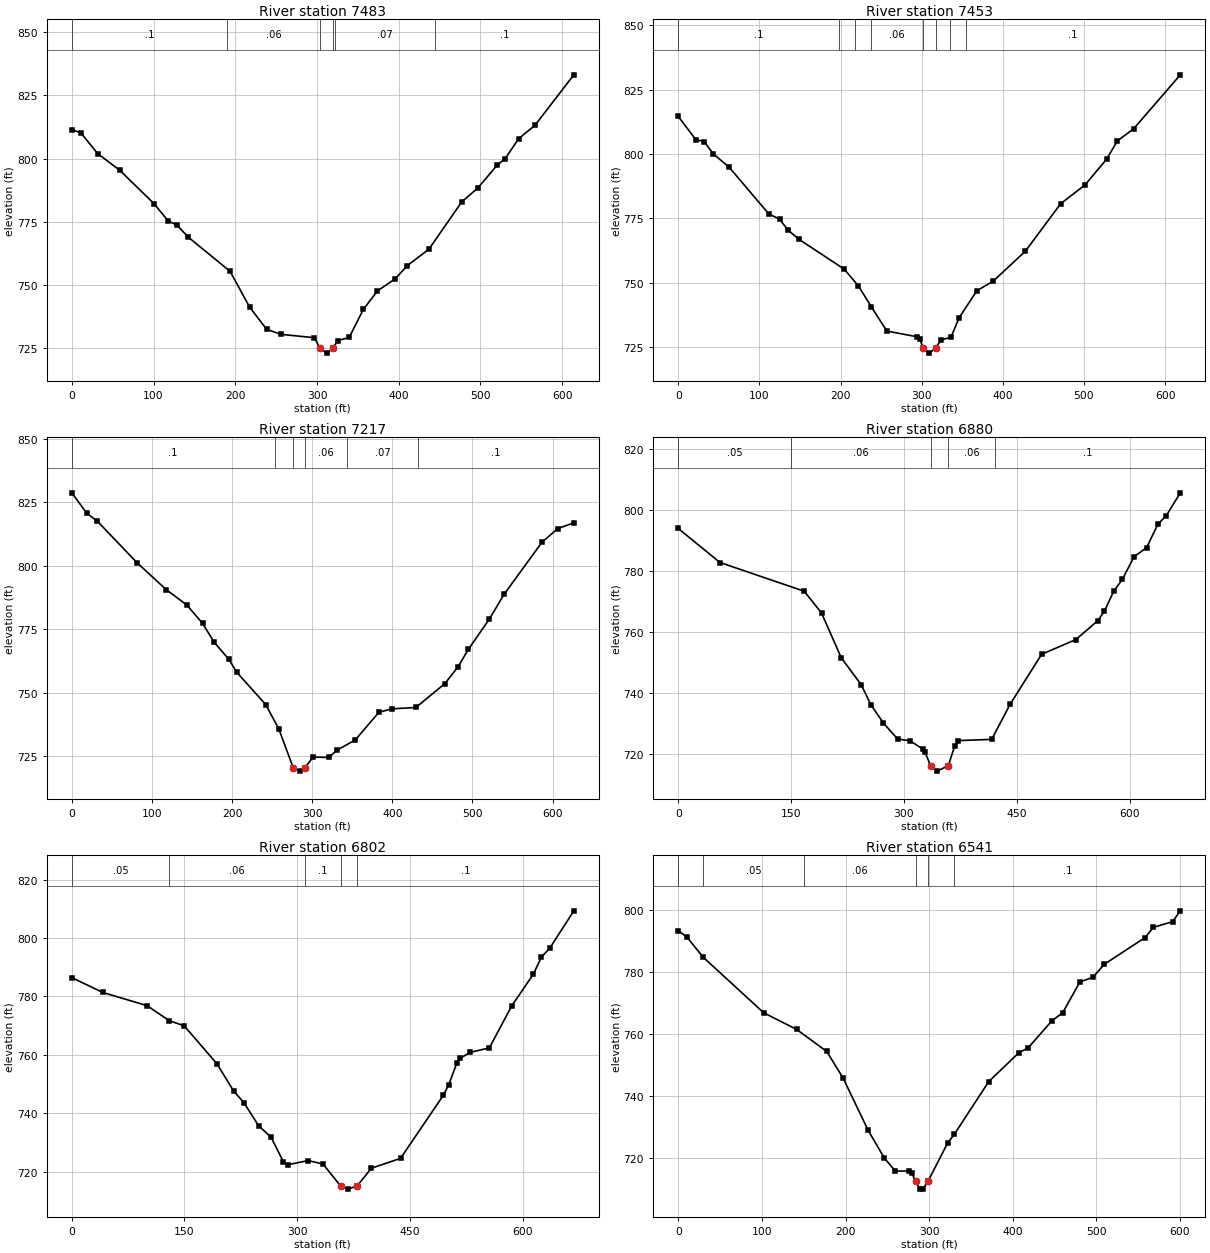
Type RM Length L Ch R = 1 ,7483    ,29.7,29.9,29.9
XS GIS Cut Line= 4
1624447.68167995552781.1015898721624677.77259244552854.635400096
1624786.76827212552911.5888617171625033.49694405552949.893990288
#Sta/Elev= 30
       0   811.5    11.1  810.19    31.7  801.97    58.6  795.39   100.6  782.15
   117.8  775.36     129  773.55   142.1  768.98   193.6  755.34   217.7  741.08
   238.4  732.35   255.9  730.35   296.9  729.01  303.84 724.765   311.8  722.91
  319.49724.7684   325.2  727.82   339.4  729.15   356.6   740.2     374  747.57
   395.6  752.34   410.5  757.59   436.9  764.09   476.9  782.77   496.9   788.4
   520.6  797.47   530.1  799.93   546.7  807.91   566.6  813.18   614.2  833.19
#Mann= 6, -1 ,  0
       0     0.1       0     190    0.06       0  303.84   0.045       0
  319.49    0.06       0  321.56    0.07       0  444.53     0.1       0
Bank Sta=303.84,319.49
XS Rating Curve= 0 ,0
Exp/Cntr(USF)=0,0
Exp/Cntr=0.3,0.1

Type RM Length L Ch R = 1 ,7453    ,238.3,235.8,232.1
XS GIS Cut Line= 6
1624434.02027627552808.1361482531624527.62081086552835.585568422
1624613.50843434552863.656050349 1624684.9600631552891.399433175
1624773.10686843552938.6234200991625023.31035276552983.183210975
#Sta/Elev= 30
       0  814.61    21.8  805.53      32  804.86    43.2  800.04    62.8  794.84
   111.7  776.65   124.8  774.68   135.2  770.42   148.8   766.8   204.3  755.27
   221.9  748.76   237.9  740.59   257.1  731.12   294.8  728.87   297.6  728.15
  301.72724.4722   309.4  722.54  317.13724.4714   323.7  727.68     336  728.65
     346  736.21   367.9  746.79   387.9  750.48   427.9  762.23   471.2  780.65
   501.2  787.95   527.9  797.98   541.2  805.12   561.2  809.81   618.7   830.8
#Mann= 8, -1 ,  0
       0     0.1       0   197.9    0.06       0   217.9     0.1       0
   237.9    0.06       0  301.72   0.045       0  317.13    0.06       0
  334.55    0.07       0  354.55     0.1       0
Bank Sta=301.72,317.13
XS Rating Curve= 0 ,0
Exp/Cntr(USF)=0,0
Exp/Cntr=0.3,0.1

Type RM Length L Ch R = 1 ,7217    ,346.6,337.9,319.9
XS GIS Cut Line= 4
1624340.89675839553123.4331156991624593.93564619 553121.07926558
1624772.82825523553131.6715911151624967.02089005553130.494666056
#Sta/Elev= 30
       0  828.71    18.9  820.62    31.9  817.54    81.6  801.11     118  790.54
   143.6   784.5   163.2  777.29   177.6  769.88   196.1  763.08   205.9  758.01
     242  745.28   258.4  735.66  276.28720.4224   284.7  719.06  291.12  720.42
   301.1  724.59   320.8  724.45   330.7  727.26   353.7  731.34   383.3  742.25
   399.6   743.6   429.3  744.13   465.4  753.49   481.8  760.07   494.9  767.05
   521.2  779.03   539.4   788.7   586.8  809.27   606.5  814.63   626.5   816.9
#Mann= 6, -1 ,  0
       0     0.1       0  253.05    0.06       0  276.28   0.045       0
  291.12    0.06       0  343.05    0.07       0  432.26     0.1       0
Bank Sta=276.28,291.12
XS Rating Curve= 0 ,0
Exp/Cntr(USF)=0,0
Exp/Cntr=0.3,0.1

Type RM Length L Ch R = 1 ,6880    ,79.4,77.5,74.6
XS GIS Cut Line= 4
1624419.28365113553514.716986988 1624709.7779671553490.393300244
1624722.28729171553391.0136658351624970.38889649553270.785157074
#Sta/Elev= 30
       0     794    55.5  782.82   167.5  773.38   190.5  766.24   216.8  751.48
   243.2  742.72   255.9  736.18   272.8  730.09   291.5  724.87   307.9  724.29
   324.7  721.64   327.8  720.71  335.38716.1235   344.3  714.31     359716.1219
   367.5  722.54   371.7  724.33   416.7  724.74   441.2  736.28     483  752.67
   528.4   757.5   557.6  763.68   566.5  766.81   578.8  773.36   590.4  777.29
   605.8  784.68   622.5  787.68   637.5  795.36   648.7   798.2   667.4   805.7
#Mann= 5, -1 ,  0
       0    0.05       0     150    0.06       0  335.38   0.045       0
     359    0.06       0  421.67     0.1       0
Bank Sta=335.38,359
XS Rating Curve= 0 ,0
Exp/Cntr(USF)=0,0
Exp/Cntr=0.3,0.1

Type RM Length L Ch R = 1 ,6802    ,245.6,261.5,273
XS GIS Cut Line= 4
1624440.48000672553556.0672544521624765.72244661553524.098980446
1624778.23177122553424.7193460371624995.75502695553320.474974279
#Sta/Elev= 30
       0  786.43    40.9  781.37   100.2  776.81   129.9  771.66   149.7   769.9
   193.3  756.87   215.6  747.51   229.3  743.54   248.6  735.69   265.1  731.83
   281.5  723.43   288.1  722.37   314.5  723.77   334.2  722.61  357.97 715.033
   367.3  713.99  379.59715.0336   398.8  721.15   437.5  724.51   494.4  746.08
   501.8  749.77   512.3  757.06   516.5  758.73   530.5  760.85   555.7  762.34
   585.4  776.68   614.2  787.55   625.1  793.49     636  796.43   668.2  809.29
#Mann= 5, -1 ,  0
       0    0.05       0     130    0.06       0     310     0.1       0
  357.97   0.045       0  379.59     0.1       0
Bank Sta=357.97,379.59
XS Rating Curve= 0 ,0
Exp/Cntr(USF)=0,0
Exp/Cntr=0.3,0.1

Type RM Length L Ch R = 1 ,6541    ,190.7,190.6,190.3
XS GIS Cut Line= 2
1624451.17023477553711.4387984511625051.40201512553706.731098213
#Sta/Elev= 30
       0  793.43    10.3  791.36      30   784.8   102.2  766.88   141.6   761.5
   177.6  754.37   197.3   745.7   226.9  728.97   246.5  719.88   259.7  715.69
   276.1  715.76   279.4  715.07  283.78712.3484   289.2  709.88   292.5  709.91
  298.52712.3527     322  724.74     330  727.54   371.2  744.64   407.3  753.97
   418.3  755.53   446.7  764.27   459.8  766.93   480.1  776.81   495.9  778.38
   509.4  782.56   558.2  791.19   568.1   794.5     591  796.33   600.3  799.84
#Mann= 6, -1 ,  0
       0    0.06       0      30    0.05       0     150    0.06       0
  283.78   0.045       0  298.52    0.06       0     330     0.1       0
Bank Sta=283.78,298.52
XS Rating Curve= 0 ,0
Exp/Cntr(USF)=0,0
Exp/Cntr=0.3,0.1