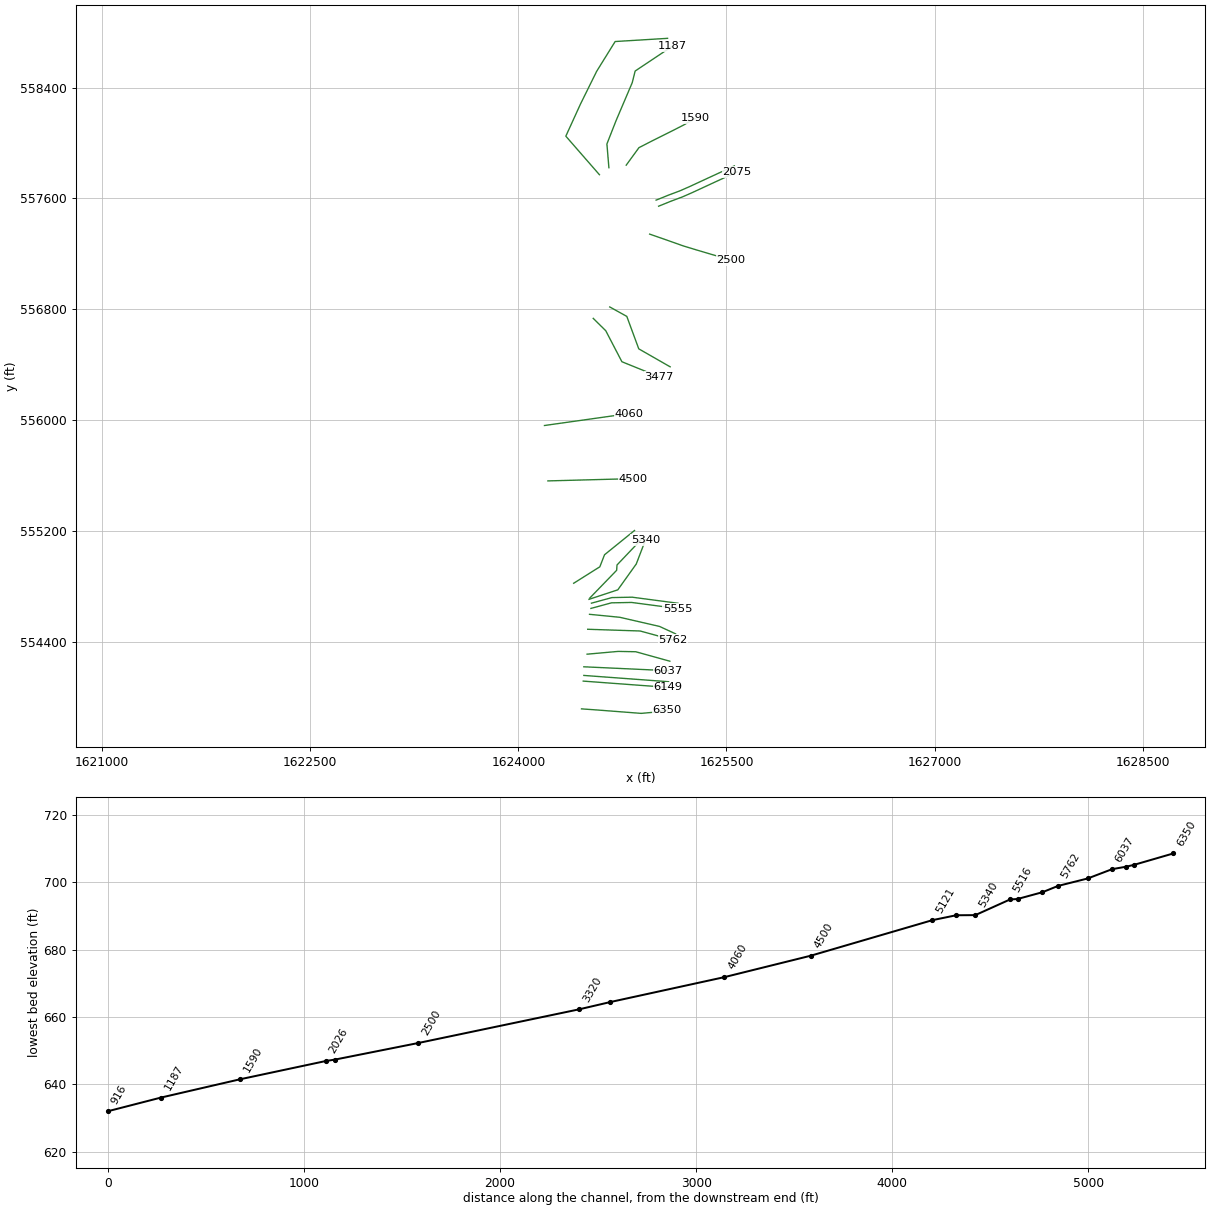
HEC-RAS study BoggsRn.prj: BoggsRn

--- BoggsRn.g01 (geometry) --- (continued)

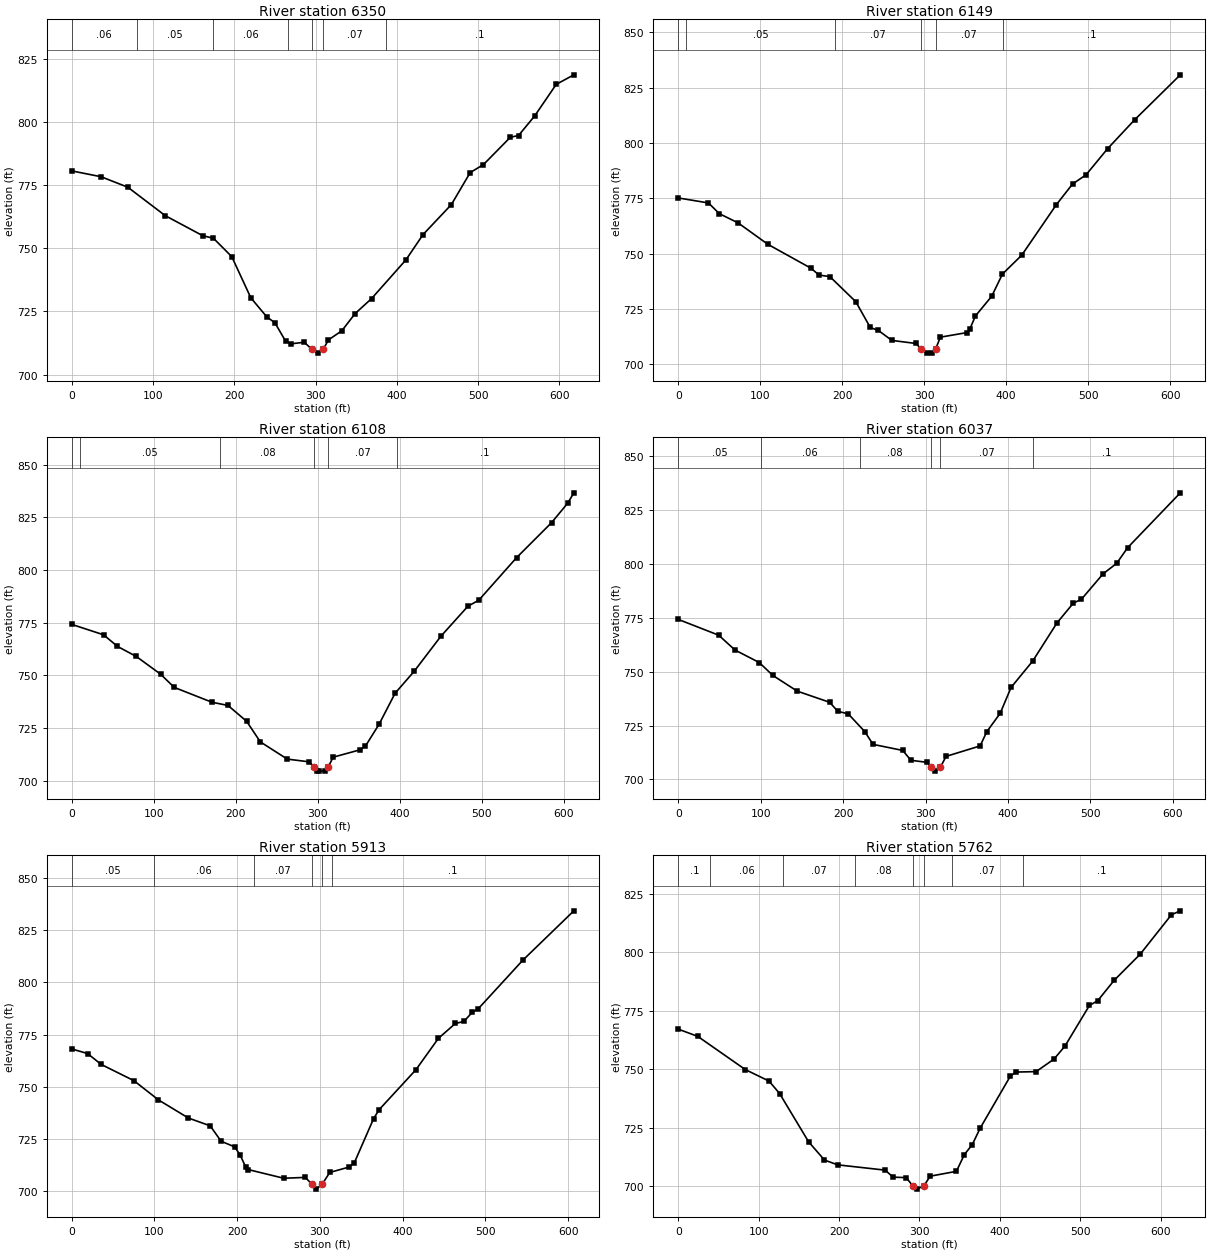
Type RM Length L Ch R = 1 ,6350    ,200.8,200.9,201
XS GIS Cut Line= 6
1624454.95858542553921.087328831 1624548.4862855553914.595543916
1624810.21279617553894.4610697571624884.99217417553888.710096995
1624973.34796859553896.5952518381625070.21818168553911.032887007
#Sta/Elev= 30
       0  780.58    36.1  778.27      69  774.12   115.1  762.87   161.2  754.94
   174.3  753.95   196.9  746.67   220.4  730.35   240.1  722.82     250   720.5
   263.2  713.22   269.7  712.18   286.2   712.8  295.46710.0054   302.6   708.5
   309.5710.0029   315.8  713.71   332.3  717.32   348.7  724.14     369  730.09
   411.2  745.37   432.3  755.39   467.2  767.27   490.3   779.9   506.7  783.09
   539.8   793.9   549.8  794.56   569.7  802.32   596.2   814.8   617.9  818.58
#Mann= 7, -1 ,  0
       0    0.06       0      80    0.05       0  173.75    0.06       0
  266.25    0.07       0  295.46   0.045       0   309.5    0.07       0
  386.25     0.1       0
Bank Sta=295.46,309.5
XS Rating Curve= 0 ,0
Exp/Cntr(USF)=0,0
Exp/Cntr=0.3,0.1

Type RM Length L Ch R = 1 ,6149    ,41.1,41.1,41.1
XS GIS Cut Line= 6
1624467.31237128   554121.298747 1624560.8059507554114.372251671
1624648.06693103554107.9086819111624722.86205704554102.367682499
 1624897.3840177554089.4402149141625078.13857746554076.050477919
#Sta/Elev= 30
       0  775.19    36.9  772.93    50.1   768.1    73.1  763.91   109.3  754.26
   161.9  743.46   171.8  740.36     185  739.66   216.6  728.33   234.3  716.69
   244.2  715.34   260.6  710.85   290.2  709.46  296.44 706.871   303.4  705.11
     310  705.19  313.87706.8673   319.8  712.31   352.7  714.42     356  716.23
   362.6  721.91   382.4  730.78   395.5  740.81   419.1  749.36   461.3  772.16
     481  781.47   497.5  785.63   523.8  797.44   556.7  810.46   612.5  830.79
#Mann= 6, -1 ,  0
       0    0.06       0      10    0.05       0  191.25    0.07       0
  296.44   0.045       0  313.87    0.07       0  396.25     0.1       0
Bank Sta=296.44,313.87
XS Rating Curve= 0 ,0
Exp/Cntr(USF)=0,0
Exp/Cntr=0.3,0.1

Type RM Length L Ch R = 1 ,6108    ,70.5,70.8,71
XS GIS Cut Line= 6
1624471.58258173554162.2107129681624565.07616115 554155.28421764
1624652.33714149554148.8206478791624727.13226749554143.279648467
1624901.65422815554130.3521808821625082.40878791554116.962443887
#Sta/Elev= 30
       0   774.2    38.8  769.27    55.7  763.76    78.6  759.01   108.3  750.59
     125   744.3   170.8  737.28   190.6  735.72   213.4  728.17     230  718.44
   262.9  710.26   289.2  708.98  295.86 706.692   299.1  704.81   302.2  704.55
     309  704.73  313.01706.6945   318.9  711.17   351.8  714.68   358.3  716.45
   374.8  726.73   394.5  741.56   417.6  751.88   450.4  768.63   483.3  782.84
   496.5  785.67   542.6  805.88   585.3  822.49   605.1  831.79   612.5  836.66
#Mann= 6, -1 ,  0
       0    0.06       0      10    0.05       0  181.25    0.08       0
  295.86   0.045       0  313.01    0.07       0  396.25     0.1       0
Bank Sta=295.86,313.01
XS Rating Curve= 0 ,0
Exp/Cntr(USF)=0,0
Exp/Cntr=0.3,0.1

Type RM Length L Ch R = 1 ,6037    ,124,124.3,124.5
XS GIS Cut Line= 2
1624471.53205115 554224.481644451625080.03592149554196.458439894
#Sta/Elev= 30
       0  774.27    49.1  766.93    68.8  760.06    98.3  754.24   114.7  748.27
   144.3  740.97   183.7  735.78   193.6  731.59   206.2  730.42   226.4  722.14
   236.3  716.25   272.4  713.43   282.2  708.86     302   707.9  306.66 705.605
   311.8  703.83  318.01705.6034   324.9  710.67   366.3  715.54   374.2  722.07
   390.6  730.68   403.8   742.7     430  754.91   459.6   772.7   479.3  781.81
   489.2  783.64   515.4  795.41   531.9  800.28   545.2  807.56   609.1  833.02
#Mann= 6, -1 ,  0
       0    0.05       0     100    0.06       0     220    0.08       0
  306.66   0.045       0  318.01    0.07       0     430     0.1       0
Bank Sta=306.66,318.01
XS Rating Curve= 0 ,0
Exp/Cntr(USF)=0,0
Exp/Cntr=0.3,0.1

Type RM Length L Ch R = 1 ,5913    ,151.5,151.4,151.3
XS GIS Cut Line= 4
1624494.93670973554315.3737961671624718.55247104554335.381522178
1624845.66037747554333.027672059 1625091.6377149554264.766018608
#Sta/Elev= 30
       0   768.1    19.1   765.9    35.6  760.69    75.1  752.94   104.8  743.73
     141  735.06   167.3  731.35   180.5  723.98     197  721.26   203.6  717.28
   210.2  711.68   213.5   710.4   256.2  706.27   282.4  706.68  290.45  703.33
   295.5  701.07  302.52703.3242   311.9  709.05   334.9  711.59   341.5  713.63
   364.9  734.83   371.7  739.14     416  758.16   443.2  773.18   463.7  780.29
   473.9  781.23     484  785.57   490.9  787.12   545.4  810.61   606.9  834.15
#Mann= 6, -1 ,  0
       0    0.05       0     100    0.06       0     220    0.07       0
  290.45   0.045       0  302.52    0.07       0  314.51     0.1       0
Bank Sta=290.45,302.52
XS Rating Curve= 0 ,0
Exp/Cntr(USF)=0,0
Exp/Cntr=0.3,0.1

Type RM Length L Ch R = 1 ,5762    ,80.9,79.3,77.9
XS GIS Cut Line= 3
1624499.51129942554494.9737664431624877.60215453554482.519008863
1625115.13217409554417.576344338
#Sta/Elev= 30
       0  767.19    24.3  764.09    83.4  749.92     113  744.99   126.1  739.67
   162.2  719.05   181.9  711.27   198.3  709.23   257.4  706.97   267.2  703.98
   283.6  703.77  291.61700.3171   296.8  698.86  305.71700.3159   313.3  704.38
     346  706.46   355.9  713.62   365.7  717.86   375.6  724.92   412.9  746.99
   419.7  748.85   445.1  749.04   467.3  754.37   480.9  759.88   511.5  777.32
   521.7   779.3   542.1  787.99   574.7  799.23   613.5  816.05   624.5  817.71
#Mann= 8, -1 ,  0
       0     0.1       0      40    0.06       0     130    0.07       0
     220    0.08       0  291.61   0.045       0  305.71    0.08       0
     340    0.07       0   428.3     0.1       0
Bank Sta=291.61,305.71
XS Rating Curve= 0 ,0
Exp/Cntr(USF)=0,0
Exp/Cntr=0.3,0.1

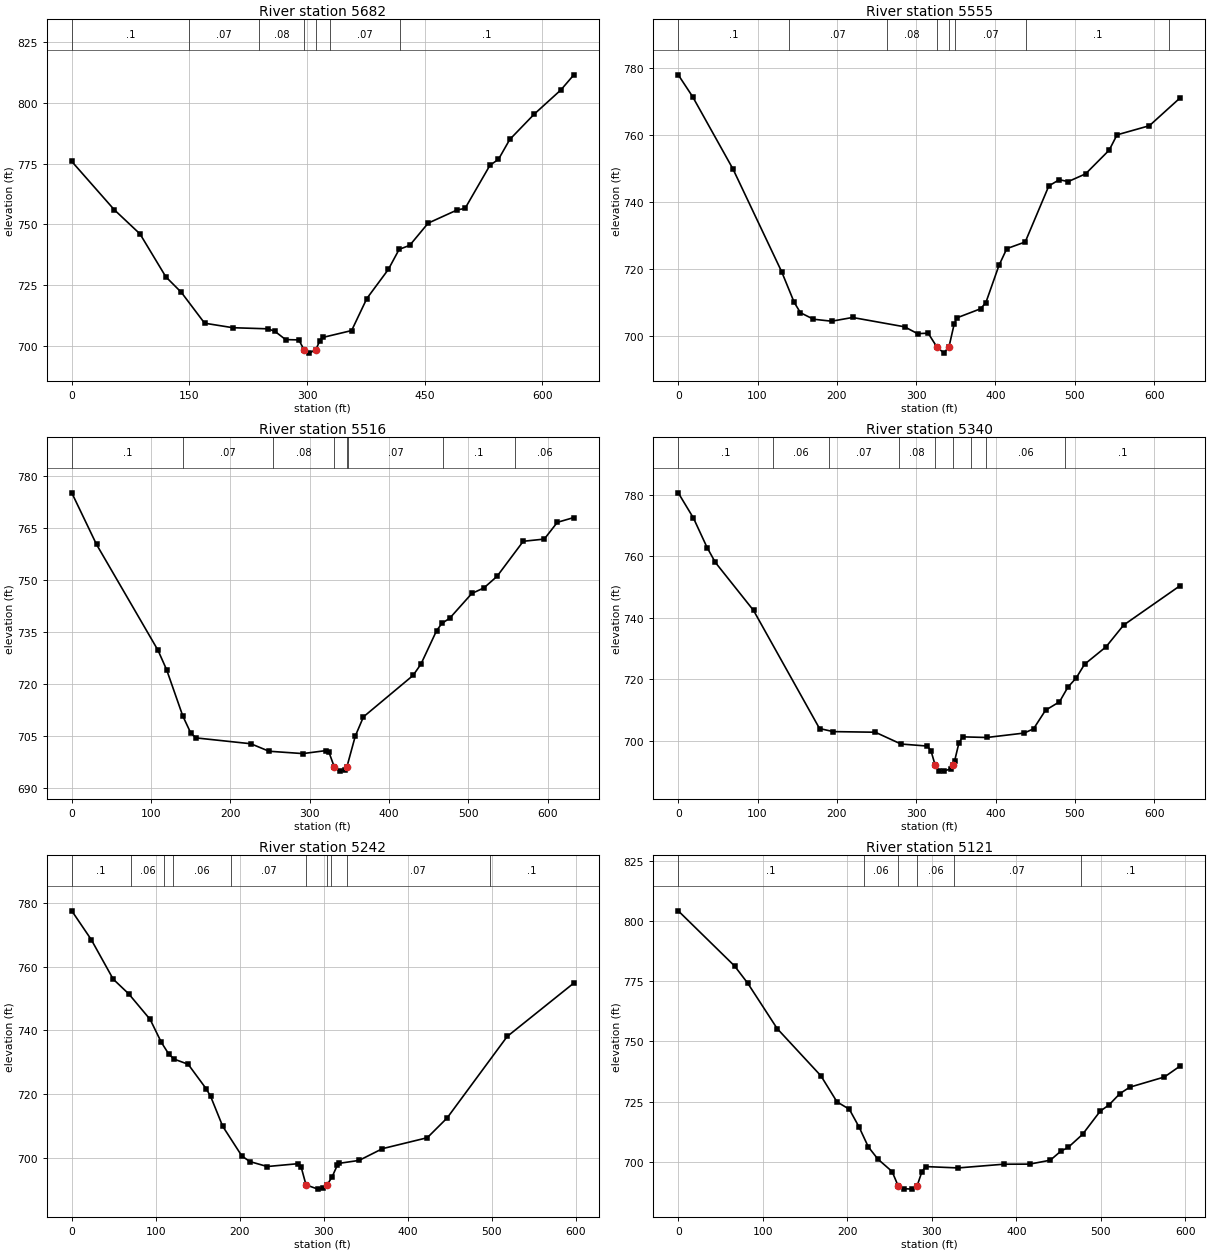
Type RM Length L Ch R = 1 ,5682    ,126.7,127.4,128
XS GIS Cut Line= 4
1624512.67944772554602.7115117881624730.63770537554581.360498794
1625017.09712971554515.528208728 1625132.7484501554462.150676241
#Sta/Elev= 30
       0  775.88    54.1  756.04      87  746.06     120  728.39   139.8  721.99
   169.4  709.32   205.4  707.46   250.4     707   259.3  705.91   272.7  702.57
   289.6  702.44  296.11698.4606     303     697  311.26 698.462   316.5  702.18
   319.9  703.44   356.9  706.29   376.3  719.48   403.7  731.43   417.5  739.71
     431  741.36   454.5   750.5   491.5  755.93   501.6  756.57   533.3  774.31
   544.2  776.77   558.6  784.95   589.8  795.37   623.7   805.3   640.3  811.54
#Mann= 7, -1 ,  0
       0     0.1       0     150    0.07       0     239    0.08       0
  296.11   0.045       0  311.26    0.08       0     329    0.07       0
     419     0.1       0
Bank Sta=296.11,311.26
XS Rating Curve= 0 ,0
Exp/Cntr(USF)=0,0
Exp/Cntr=0.3,0.1

Type RM Length L Ch R = 1 ,5555    ,38.2,38.4,38.5
XS GIS Cut Line= 4
1624522.72322257554645.2132937821624670.75023047554685.521117528
1624815.99738845554688.3009674421625147.49449064554644.518331303
#Sta/Elev= 30
       0  777.89    18.1   771.4    69.1   749.8   130.4  719.24   146.2  710.11
   154.1  707.02   170.5  705.08   193.5  704.49   219.8   705.6   285.4  702.82
   301.8  700.78   315.1  700.93  325.81696.9437   334.9  694.98  341.49696.9445
   348.1   703.8   351.5   705.5   381.2  708.19   387.9  710.02   404.4  721.09
   414.3  726.11   437.5  728.09   467.3  744.79   480.5  746.65   491.7  746.08
   513.6  748.38   543.4  755.45   553.3  760.01   594.1  762.73   633.1  771.07
#Mann= 8, -1 ,  0
       0     0.1       0     140    0.07       0  263.42    0.08       0
  325.81   0.045       0  341.49    0.08       0  348.69    0.07       0
  438.69     0.1       0  618.69    0.06       0
Bank Sta=325.81,341.49
XS Rating Curve= 0 ,0
Exp/Cntr(USF)=0,0
Exp/Cntr=0.3,0.1

Type RM Length L Ch R = 1 ,5516    ,165.3,176.9,189.2
XS GIS Cut Line= 4
1624526.54551621554683.088748854 1624674.5725241  554723.3965726
1624819.81968208554726.1764225141625151.31678428554682.393786376
#Sta/Elev= 30
       0  775.14    31.2  760.25   108.7  729.72   119.6   724.1     140  710.75
   150.2  705.76   156.9  704.42   225.8  702.74   248.7  700.58   291.4   699.9
   321.1  700.78   324.4  700.23  330.94696.0954   337.7  694.84   344.3   695.1
  346.97 696.097   357.5  704.95   367.8   710.5   430.3  722.44   440.3  725.72
   460.1  735.41   466.7  737.45   476.7  738.99   504.5  746.11   519.7   747.7
   536.2  751.03   569.3  761.16   595.8  761.79   612.3  766.63   633.1  768.01
#Mann= 8, -1 ,  0
       0     0.1       0     140    0.07       0  253.42    0.08       0
  330.94   0.045       0  346.97    0.08       0  348.69    0.07       0
  468.69     0.1       0  558.69    0.06       0
Bank Sta=330.94,346.97
XS Rating Curve= 0 ,0
Exp/Cntr(USF)=0,0
Exp/Cntr=0.3,0.1

Type RM Length L Ch R = 1 ,5340    ,91.5,97.4,104.1
XS GIS Cut Line= 4
1624508.91200776554710.7639468321624716.44304653554779.168032235
 1624849.7730435554965.8300279951624915.85834634555138.579328419
#Sta/Elev= 30
       0  780.55    19.2  772.35    36.4  762.78    46.8  757.95    94.9  742.38
   178.1  704.03   195.3  703.03   248.4  702.83   280.8     699   313.8  698.34
   318.5  696.89  323.83692.1723   328.2  690.38   334.9   690.2   344.4  691.04
   346.4692.1705   348.4  693.51   353.7  699.23   358.4  701.33     389  701.12
   436.1  702.56   447.9  703.93     463  709.97   480.6   712.7   491.1  717.42
   501.7  720.46   512.2  724.89   539.3  730.56   561.4   737.6   632.9  750.45
#Mann= 9, -1 ,  0
       0     0.1       0     120    0.06       0     190    0.07       0
  278.51    0.08       0  323.83   0.045       0   346.4    0.08       0
  368.51    0.07       0  388.51    0.06       0   487.9     0.1       0
Bank Sta=323.83,346.4
XS Rating Curve= 0 ,0
Exp/Cntr(USF)=0,0
Exp/Cntr=0.3,0.1

Type RM Length L Ch R = 1 ,5242    ,125.8,121.2,116.8
XS GIS Cut Line= 4
1624514.30023133554719.7066249471624708.32608989554920.132139871
1624710.79758679554958.3571520391624903.94572789555161.450419023
#Sta/Elev= 30
       0  777.59    23.1  768.58    49.3  756.13    67.8   751.5    93.3  743.46
   106.5  736.32   115.7  732.47   122.2  730.96   138.5  729.39   159.9  721.71
   165.3  719.26   179.6  709.91   202.4  700.58   211.8  698.83   232.6  697.26
   269.7  698.16   273.1  696.98  278.76 691.496   292.9  690.16   299.5  690.38
  303.85 691.496   309.8  693.99   315.9  697.61   318.6  698.28   341.9  699.18
   369.7  702.87   423.1  706.31   446.7  712.52   518.2  738.12   597.5   754.9
#Mann= 10, -1 ,  0
       0     0.1       0      70    0.06       0     110     0.1       0
     120    0.06       0     190    0.07       0  278.76   0.045       0
  303.85    0.07       0  308.96    0.08       0  327.26    0.07       0
  497.26     0.1       0
Bank Sta=278.76,303.85
XS Rating Curve= 0 ,0
Exp/Cntr(USF)=0,0
Exp/Cntr=0.3,0.1

Type RM Length L Ch R = 1 ,5121    ,628.4,620.9,611.7
XS GIS Cut Line= 4
1624398.46823325554826.6367649411624587.01162779554945.270810939
 1624620.9070695 555032.127880331624836.99051043555206.901251667
#Sta/Elev= 30
       0  804.23    66.7  781.32    82.2  774.18   117.1  755.32   168.8  735.73
   187.8  724.93   202.4  721.86     214  714.43   224.8  706.27   236.2  701.16
     253     696  260.04690.1273   267.1  688.89   276.8  688.71  282.62690.1277
   288.2   695.9   292.6  698.07   331.2  697.51   384.8  699.05   415.7  699.09
   440.1  700.72   452.7   704.5   461.2  706.01   478.2  711.42   499.1  721.05
   509.6  723.69   522.5  728.37   534.1  731.02   575.1  735.26   593.9  739.87
#Mann= 6, -1 ,  0
       0     0.1       0     220    0.06       0  260.04   0.045       0
  282.62    0.06       0     326    0.07       0     476     0.1       0
Bank Sta=260.04,282.62
XS Rating Curve= 0 ,0
Exp/Cntr(USF)=0,0
Exp/Cntr=0.3,0.1

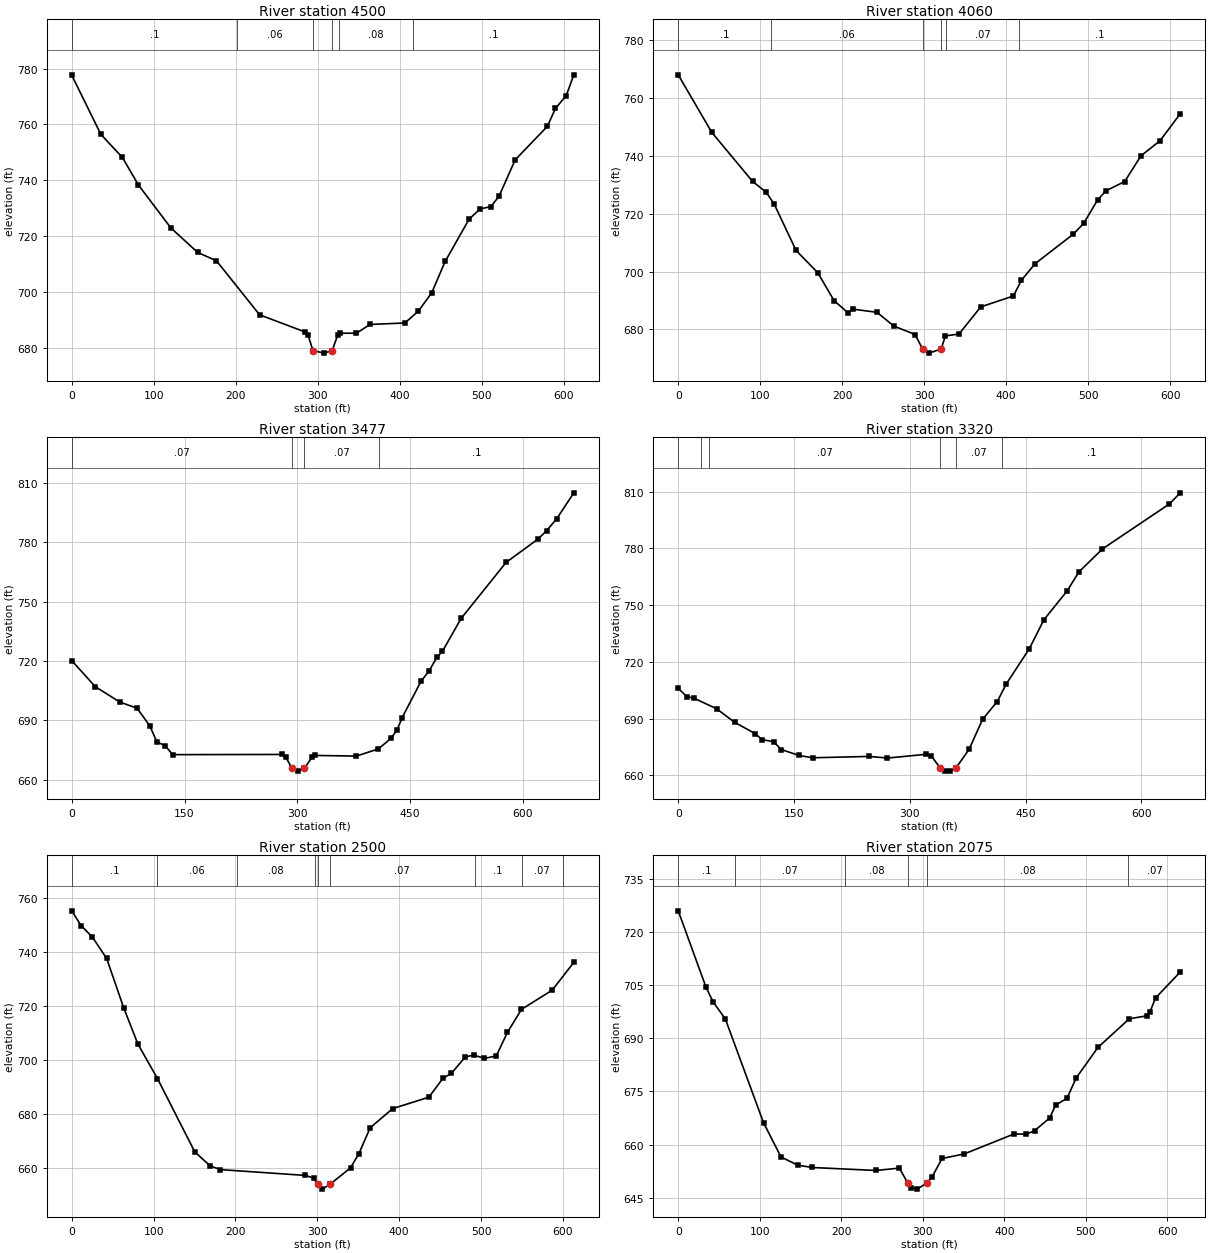
Type RM Length L Ch R = 1 ,4500    ,437.8,439.5,440.6
XS GIS Cut Line= 6
 1624212.8255893555564.3940898931624306.54259346555566.886210889
1624568.94954897555573.865527645 1624643.9231523555575.859618142
1624731.39246556555578.1857289821624825.08289497555581.666693136
#Sta/Elev= 30
       0  777.61    35.4  756.49    61.7   748.2    81.4  738.29   120.8     723
   153.6  714.18   176.5  711.21   229.1  691.88   284.9   685.7   288.1  684.76
  294.19 679.089   307.8  678.16  317.75679.0855   324.2  684.48   327.5  685.29
   347.2  685.28   363.9  688.43   406.3  688.94   422.7  693.15   439.1  699.72
   455.5  710.98   484.8  726.13   498.2  729.76   511.3   730.6   521.2  734.28
   540.9  747.32   580.2  759.31   590.1  765.72   603.2  770.34   612.5  777.75
#Mann= 6, -1 ,  0
       0     0.1       0  201.25    0.06       0  294.19   0.045       0
  317.75    0.07       0  326.25    0.08       0  416.25     0.1       0
Bank Sta=294.19,317.75
XS Rating Curve= 0 ,0
Exp/Cntr(USF)=0,0
Exp/Cntr=0.3,0.1

Type RM Length L Ch R = 1 ,4060    ,596.1,583.6,571.2
XS GIS Cut Line= 6
1624187.93303782555963.7104035191624280.76224848555976.815692278
1624367.40315132 555989.047623191624614.94858798 556023.99505985
1624701.58949081556036.2263346041624794.41902956556049.330311018
#Sta/Elev= 30
       0  767.99      41  748.07    90.7  731.16   107.3  727.41   117.2  723.26
   143.7  707.31   170.2  699.63   190.1  689.97   206.7  685.85   213.5     687
   242.5  685.92     263  681.17     289  678.25  298.04673.2657   306.1  671.82
  320.75673.2637     326  677.78   342.5  678.42     369  687.79   408.8  691.56
   418.7     697   435.3  702.72   481.7  712.87   494.7  716.69   511.5  724.71
   521.7  727.91   544.6  731.11   564.5     740   587.7  745.18   612.5  754.57
#Mann= 6, -1 ,  0
       0     0.1       0  113.75    0.06       0  298.04   0.045       0
  320.75    0.06       0  326.25    0.07       0  416.25     0.1       0
Bank Sta=298.04,320.75
XS Rating Curve= 0 ,0
Exp/Cntr(USF)=0,0
Exp/Cntr=0.3,0.1

Type RM Length L Ch R = 1 ,3477    ,157.7,156.7,155.4
XS GIS Cut Line= 4
1624539.42255928556735.9060484531624629.65348051556646.982821735
1624746.03829195556423.3670604291625014.11566662556314.828416053
#Sta/Elev= 30
       0  720.16    31.2  707.08    63.7  699.29    86.9  696.16   103.8  687.27
   113.2  679.19     124  677.27   134.5  672.73   279.6  672.82   284.4  671.66
  293.12665.7501   300.9  664.41  309.48665.7488   319.4  671.29   323.8  672.33
   378.6     672     408  675.62   424.7  680.95   432.8  685.17   439.5  691.34
   464.7  709.78   475.1   714.8   485.9  721.89     493  724.78   518.2  741.56
   577.9  769.74   620.4  781.53   631.9  785.78   645.2  791.77     668  804.84
#Mann= 4, -1 ,  0
       0    0.07       0  293.12   0.045       0  309.48    0.07       0
  408.77     0.1       0
Bank Sta=293.12,309.48
XS Rating Curve= 0 ,0
Exp/Cntr(USF)=0,0
Exp/Cntr=0.3,0.1

Type RM Length L Ch R = 1 ,3320    ,812.8,820.5,829.9
XS GIS Cut Line= 4
1624658.42275974556818.2908026191624781.34604374556750.290688069
1624867.65388143556516.2133706791625093.88503176556386.751614133
#Sta/Elev= 30
       0  706.02    11.1  701.68      20   700.9    49.7  695.25    73.1  688.08
    99.7  682.11   108.6  678.96   123.6  677.81   133.5   673.7   156.6  670.56
     174  669.34   247.5  670.05     271  669.19   320.9  671.15   327.9  670.36
  339.38663.9424   345.1  662.36   352.4  662.28  359.92663.9422   376.9  673.84
   394.5  689.74   413.4  699.05   424.8  708.16     455  727.05   473.9  742.33
   504.1  757.63   519.2   767.6   549.7  779.74   636.3  803.47   650.6   809.4
#Mann= 6, -1 ,  0
       0    0.07       0      30    0.06       0      40    0.07       0
  339.38   0.045       0  359.92    0.07       0  419.96     0.1       0
Bank Sta=339.38,359.92
XS Rating Curve= 0 ,0
Exp/Cntr(USF)=0,0
Exp/Cntr=0.3,0.1

Type RM Length L Ch R = 1 ,2500    ,417.3,424.2,429.9
XS GIS Cut Line= 6
1624946.17681289557343.2638917271625035.06738314557312.404701471
1625117.89792614 557283.260074721625188.68977931557258.123970151
1625284.38184513557229.0823615641625530.07393906 557156.28427881
#Sta/Elev= 30
       0  755.16    11.3  749.73    25.2  745.44    42.6  737.57    63.4  719.34
    80.8   705.9   104.7  693.15   150.3  666.04     169  660.91   181.6   659.5
   285.3  657.36   295.3  656.41  300.18654.0483   306.2  652.29  315.35 654.045
   340.5  660.16   350.8  665.44   364.5  674.97   391.9  682.04   436.3  686.29
   453.4  693.28   463.7  695.07   480.8  701.19   491.1  701.83   504.1  700.63
   518.5  701.51   532.2  710.24   549.3  718.73   586.9  725.84   613.3  736.12
#Mann= 9, -1 ,  0
       0     0.1       0  104.09    0.06       0   201.9    0.08       0
  297.03    0.07       0  300.18   0.045       0  315.35    0.07       0
  492.03     0.1       0  549.53    0.07       0  599.53     0.1       0
Bank Sta=300.18,315.35
XS Rating Curve= 0 ,0
Exp/Cntr(USF)=0,0
Exp/Cntr=0.3,0.1

Type RM Length L Ch R = 1 ,2075    ,48.9,49.1,48.6
XS GIS Cut Line= 6
1625010.74980644557544.4324839421625100.52226469557580.791663185
1625182.73502678557611.5940950221625251.41828835557641.757092432
1625410.22538545557715.2782708561625574.70373102557791.425756351
#Sta/Elev= 30
       0  726.11    33.9  704.61    42.6  700.41    57.8  695.51   104.6  666.18
   126.1  656.46   146.5  654.18   164.2   653.5   242.6  652.66   271.3  653.33
   281.7  649.05   285.8   647.8     293  647.38  304.74649.0513   311.1  650.73
   323.7  656.05   350.9  657.34   412.3  663.02   426.8  662.89   437.4  663.96
   455.7  667.51   462.9  671.14   476.9  673.07   488.2  678.85   514.9  687.47
   553.3  695.58     575  696.41   578.6  697.47   585.6  701.48   615.9  708.82
#Mann= 6, -1 ,  0
       0     0.1       0      70    0.07       0  204.65    0.08       0
   281.7   0.045       0  304.74    0.08       0  552.16    0.07       0
Bank Sta=281.7,304.74
XS Rating Curve= 0 ,0
Exp/Cntr(USF)=0,0
Exp/Cntr=0.3,0.1

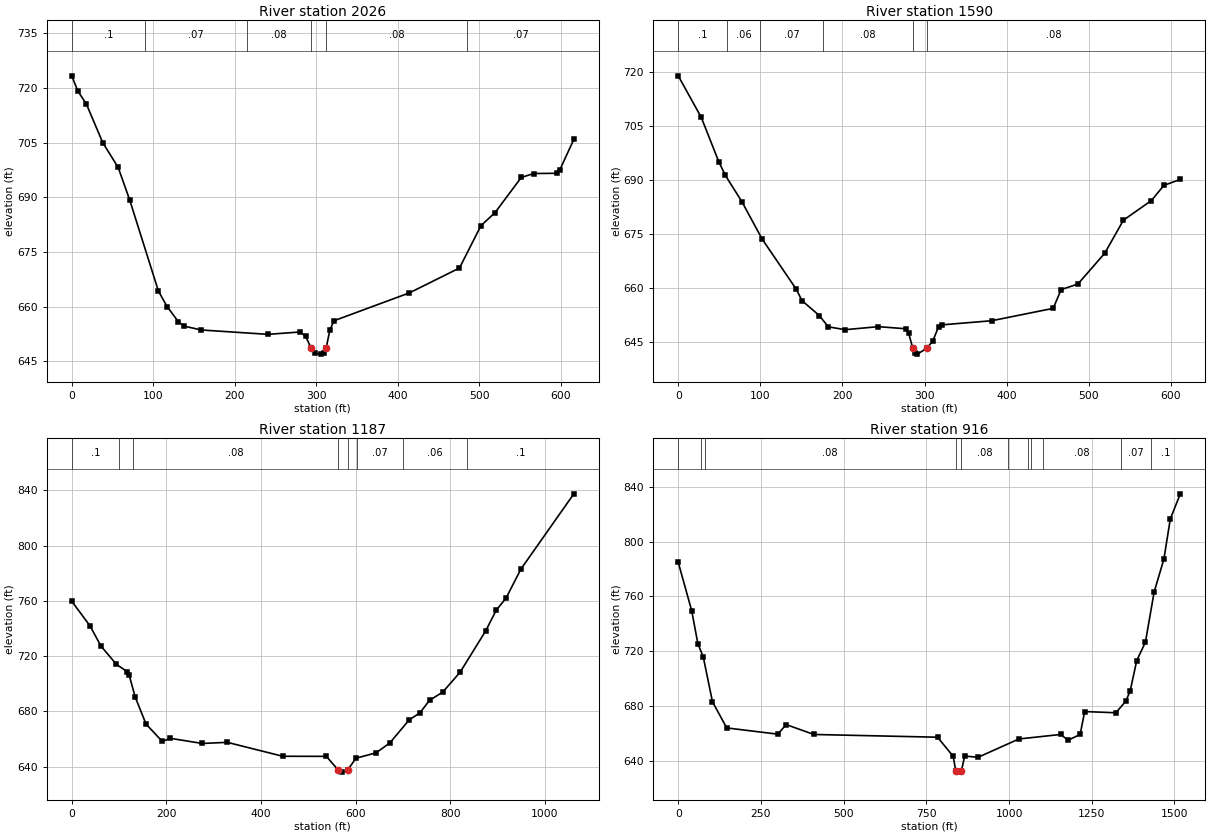
Type RM Length L Ch R = 1 ,2026    ,435,436,436.3
XS GIS Cut Line= 6
1624992.73962327557588.2221216831625082.51208152557624.581300926
1625164.72484361557655.3837327631625233.40810518557685.546730173
1625392.21520228557759.0679085971625556.69354785557835.215394092
#Sta/Elev= 30
       0  723.34     7.3  719.23      18  715.55      38  704.99    56.9   698.2
    71.1  689.23   106.3  664.24   116.9     660   130.9  655.79   137.9  654.61
   158.9  653.56   240.7  652.36   280.3  653.01     287  651.78  293.49648.6313
   298.4  647.15   305.6  646.93   309.3  647.19  312.06 648.634   316.6  653.52
   321.6  656.09   414.1  663.74   475.6  670.57     502  682.22   519.3   685.8
   551.4  695.44   566.8  696.52   594.9  696.58   598.5  697.43   615.9   705.9
#Mann= 6, -1 ,  0
       0     0.1       0      90    0.07       0  214.65    0.08       0
  293.49   0.045       0  312.06    0.08       0  484.66    0.07       0
Bank Sta=293.49,312.06
XS Rating Curve= 0 ,0
Exp/Cntr(USF)=0,0
Exp/Cntr=0.3,0.1

Type RM Length L Ch R = 1 ,1590    ,396.7,403.8,410.7
XS GIS Cut Line= 6
1624777.12865461 557840.31999945 1624868.8422887557966.312812146
1624957.16729484558011.8112551971625113.69126001558090.074878196
1625191.56249534558129.9888403671625272.70701809558177.262695949
#Sta/Elev= 30
       0  718.84    28.1  707.27    49.3  695.03    57.4  691.19    77.7  683.82
   102.1  673.53   143.8  659.55   150.8  656.37   171.9  652.24   182.7  649.12
   203.2  648.32   243.8  649.16   276.9  648.58   280.6  647.41  285.71643.1609
   287.9  641.83   291.4  641.53  302.64643.1616   309.9  645.07   317.2  649.17
   320.7  649.65   381.9  650.81   456.8  654.25   466.4  659.47   486.8  660.99
   519.5  669.55   542.3  678.74   576.4   684.2   591.6   688.4   611.6  690.07
#Mann= 6, -1 ,  0
       0     0.1       0      60    0.06       0     100    0.07       0
  175.84    0.08       0  285.71   0.045       0  302.64    0.08       0
Bank Sta=285.71,302.64
XS Rating Curve= 0 ,0
Exp/Cntr(USF)=0,0
Exp/Cntr=0.3,0.1

Type RM Length L Ch R = 1 ,1187    ,271.1,270.6,270
XS GIS Cut Line= 6
1624652.27885232557822.0757850671624638.01541392557993.352086205
1624704.56760569558162.6433333011624820.57483903558434.915623449
1624841.56252871558518.8663821521625112.29226869558699.480818267
#Sta/Elev= 30
       0   759.7    38.6  741.89    61.6  727.33    94.5  714.04   117.6  708.68
   121.2  706.57     134  690.55   157.1  670.83   191.3  658.35   208.6  660.54
   275.9  656.84   328.8  657.65   446.2  647.57   538.4  647.51  563.43637.6195
   570.6   636.1  583.31637.6171   600.9  646.17   643.4  650.03   672.6  657.23
   713.7  673.94   736.3  678.99   756.6  688.08   784.2  693.91     821  708.27
   874.9  738.06   897.8  753.36   918.3  761.99   949.8     783  1061.7  837.43
#Mann= 8, -1 ,  0
       0     0.1       0     100    0.06       0     130    0.08       0
  563.43   0.045       0  583.31    0.08       0  603.77    0.07       0
  699.73    0.06       0  836.26     0.1       0
Bank Sta=563.43,583.31
XS Rating Curve= 0 ,0
Exp/Cntr(USF)=0,0
Exp/Cntr=0.3,0.1

Type RM Length L Ch R = 1 ,916     ,0,0,0
XS GIS Cut Line= 6
1624584.10559097557771.4236974861624341.84767755558049.252884671
1624447.68451922558281.1484368661624563.95758063558516.492454372
1624697.38272829 558731.442490111625075.33146891558754.484706915
#Sta/Elev= 30
       0  784.88    40.8  749.52    59.4  725.55    75.6  716.02   103.5  683.29
   146.6  664.25   301.2  659.69   326.3  666.68     410  659.48   783.8  657.48
   831.3  643.56  838.64633.2355   847.3  632.05  856.23633.2295     866  643.72
   906.8  642.91  1029.9   656.2  1155.9  659.48  1178.9  655.29  1215.1  659.55
  1228.6  676.17  1323.1  675.29  1353.1  683.81  1366.3  691.29  1386.1  713.32
  1412.3  726.69  1438.6  763.15  1468.2  787.27  1487.6  816.53  1517.8  834.77
#Mann= 11, -1 ,  0
       0     0.1       0      70    0.07       0      80    0.08       0
  838.64   0.045       0  856.23    0.08       0  997.57    0.07       0
 1057.57    0.08       0 1067.57    0.07       0 1101.95    0.08       0
 1339.14    0.07       0 1429.14     0.1       0
Bank Sta=838.64,856.23
XS Rating Curve= 0 ,0
Exp/Cntr(USF)=0,0
Exp/Cntr=0.3,0.1
LCMann Table=0

Chan Stop Cuts=-1
Use User Specified Reach Order=0
Composite Channel Slope=5